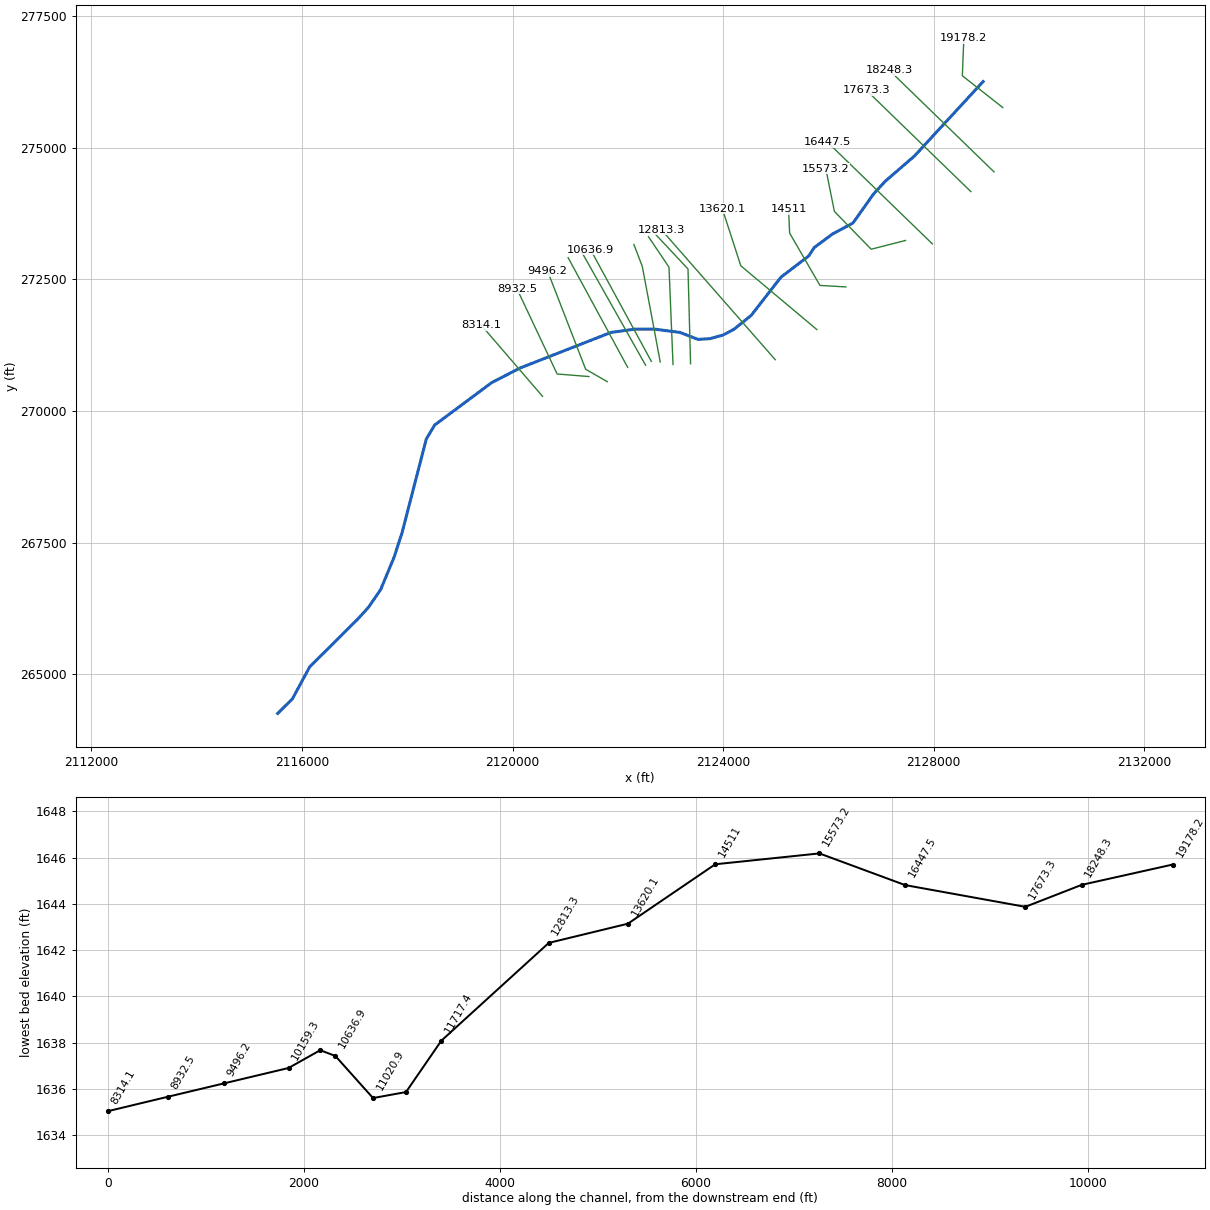
--- GREENBRRV2.prj (project) ---

Proj Title=GREENBRRV2
Current Plan=p06
Default Exp/Contr=0,0
English Units
Geom File=g02
Flow File=f01
Flow File=f02
Flow File=f04
Plan File=p04
Plan File=p05
Plan File=p06
Y Axis Title=Elevation
X Axis Title(PF)=Main Channel Distance
X Axis Title(XS)=Station
BEGIN DESCRIPTION:
Greenbrier River 2
Greenbrier County, WV
WV Disaster Studies / PMR
WVDHSEM-2017-2, Flood Risk Project
HEC-RAS Version: 5.0.7
Upstream Extents: Approximately 9,000 feet upstream of Seneca Trail S
Downstream Extents: Approximately 10,000 feet downstream of Seneca Trail S
General Notes: Calibrated primarily via Channel Manning's, i.e. 0.03 at straight reaches, 0.035-0.045 where there are significant islands.
Flows computed are based on the Alderson gage at the downstream of the reach. Gage weighting was done based off the upstream of a gage equation for all the flow frequencies.
END DESCRIPTION:
DSS Export Rating Curves= 0
DSS Export Rating Curve Sorted= 0
DSS Export Volume Flow Curves= 0
DXF OffsetX= 0
DXF OffsetY= 0
DXF ScaleX= 0
DXF ScaleY= 0

--- GREENBRRV2.p06 (plan) ---

Plan Title=Multiprofile
Program Version=5.03
Short Identifier=Multi
Geom File=g02
Flow File=f02
Subcritical Flow
K Sum by GR= 0
Std Step Tol= 0.01
Critical Tol= 0.01
Num of Std Step Trials= 20
Max Error Tol= 0.3
Flow Tol Ratio= 0.001
Split Flow NTrial= 30
Split Flow Tol= 0.02
Split Flow Ratio= 0.02
Log Output Level= 0
Friction Slope Method= 1
Unsteady Friction Slope Method= 2
Unsteady Bridges Friction Slope Method= 1
Parabolic Critical Depth
Global Vel Dist= 0 , 0 , 0
Global Log Level= 0
CheckData=False
Encroach Param=-1 ,0,0, 0
Computation Interval=0.1SEC
Output Interval=1MIN
Instantaneous Interval=Max Profile
Mapping Interval=1HOUR
Run HTab= 0
Run UNet= 0
Run Sediment= 0
Run PostProcess= 0
Run WQNet= 0
Run RASMapper= 0
UNET Theta= 0
UNET Theta Warmup= 0
UNET ZTol= 0
UNET ZSATol= 0
UNET MxIter= 0
UNET Max Iter WO Improvement= 0
UNET MaxInSteps= 0
UNET DtIC= 0
UNET DtMin= 0
UNET MaxCRTS= 0
UNET WFStab= 0
UNET SFStab= 0
UNET WFX= 1
UNET SFX= 1
UNET DSS MLevel= 1
UNET Pardiso=0
UNET DZMax Abort= 0
UNET Use Existing IB Tables= 0
UNET Froude Reduction=False
UNET Froude Limit= 0
UNET Froude Power= 0
UNET Time Slicing=0,0, 5
UNET D1 Cores= 0
UNET D2 Coriolis=0
UNET D2 Cores= 0
UNET D2 Theta= 1
UNET D2 Theta Warmup= 1
UNET D2 Z Tol= 0.01
UNET D2 Volume Tol= 0.01
UNET D2 Max Iterations= 20
UNET D2 Equation= 0
UNET D2 RampUpFraction=0.1
UNET D2 TimeSlices= 1
UNET D2 BCVolumeCheck=0
UNET D1D2 MaxIter= 0
UNET D1D2 ZTol=0.01
UNET D1D2 QTol=0.1
UNET D1D2 MinQTol=1
DSS File=dss
Write IC File= 0
Write IC File at Fixed DateTime=0
Write IC File at Sim End=0
Echo Input=False
Echo Parameters=False
Echo Output=False
Write Detailed= 0
HDF Write Warmup=0
HDF Write Time Slices=0
HDF Flush=0
HDF Face Node Velocities=0
HDF Compression= 1
HDF Chunk Size= 1
HDF Spatial Parts= 1
HDF Use Max Rows=0
HDF Fixed Rows= 1
Calibration Method= 0
Calibration Iterations= 20
Calibration Max Change=0.05
Calibration Tolerance=0.2
Calibration Maximum=1.5
Calibration Minimum=0.5
Calibration Optimization Method= 1
WQ AD Non Conservative
WQ ULTIMATE=-1
WQ Max Comp Step=1HOUR
WQ Output Interval=15MIN
WQ Output Selected Increments= 0
WQ Output face flow=0
WQ Output face velocity=0
WQ Output face area=0
WQ Output face dispersion=0
WQ Output cell volume=0
WQ Output cell surface area=0
WQ Output cell continuity=0
WQ Output cumulative cell continuity=0
WQ Output face conc=0
WQ Output face dconc_dx=0
WQ Output face courant=0
WQ Output face peclet=0
WQ Output face adv mass=0
WQ Output face disp mass=0
WQ Output cell mass=0
WQ Output cell source sink temp=0
WQ Output nsm pathways=0
WQ Output nsm derived pathways=0
WQ Output MaxMinRange=-1
WQ Daily Max Min Mean=-1
WQ Daily Range=0
WQ Daily Time=0
WQ Create Restart=0
WQ Fixed Restart=0
WQ System Summary=0
WQ Write To DSS=0
WQ Use Fixed Temperature=0
Sorting and Armoring Iterations= 10
XS Update Threshold= 0.02
Bed Roughness Predictor= 0
Hydraulics Update Threshold= 0.02
Energy Slope Method= 1
Volume Change Method= 1
Sediment Retention Method= 0
XS Weighting Method= 0
Number of US Weighted Cross Sections= 1
Number of DS Weighted Cross Sections= 1
Upstream XS Weight=0
Main XS Weight=1
Downstream XS Weight=0
Number of DS XS's Weighted with US Boundary= 1
Upstream Boundary Weight= 1
Weight of XSs Associated with US Boundary= 0
Number of US XS's Weighted with DS Boundary= 1
Downstream Boundary Weight= 0.5
Weight of XSs Associated with DS Boundary= 0.5
Percentile Method= 0
Sediment Output Level= 4
Mass or Volume Output= 0
Output Increment Type= 1
Profile and TS Output Increment= 1
XS Output Flag= 0
XS Output Increment= 10
Write Gradation File= 0
Read Gradation Hotstart= 0
Write HDF5 File= 1
Write DSS Sediment File= 0
SV Curve= 0
Specific Gage Flag= 0

--- GREENBRRV2.p01 (plan) ---

Plan Title=Floodplain
Program Version=4.00
Geom File=g01
Flow File=f01
K Sum by GR=0
Std Step Tol=0.01
Critical Tol=0.01
Num of Std Step Trials=20
Max Error Tol=0.3
Flow Tol Ratio=0.001
Split Flow NTrial=30
Split Flow Tol=0.02
Split Flow Ratio=0.02
Log Output Level=0
Friction Slope Method=1
Unsteady Friction Slope Method=2
Unsteady Bridges Friction Slope Method=1
Global Log Level=0
CheckData=False
Run HTab=0
Run UNet=0
Run PostProcess=0
UNET Theta=0
UNET Theta Warmup=0
UNET ZTol=0
UNET ZSATol=0
UNET MxIter=0
UNET MaxInSteps=0
UNET DtIC=0
UNET DtMin=0
UNET MaxCRTS=0
UNET WFStab=0
UNET SFStab=0
UNET WFX=0
UNET SFX=0
UNET DSS MLevel=0
UNET DZMax Abort=0
UNET Convert EG Bridges=0
UNET Use Existing IB Tables=0
UNET Froude Limit=0
UNET Froude Power=0
Write IC File=0
Echo Input=False
Echo Output=False
Write Detailed=0

--- GREENBRRV2.p04 (plan) ---

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Plan Title=Floodway
Program Version=5.07
Short Identifier=FW
Geom File=g02
Flow File=f01
CheckData=True
Encroach Param=-1 ,0,0, 2
Encroach River=GREENBRRV2
Encroach Reach=Main
Encroach Node=19178.2
       1   383.5   724.4
Encroach Node=18248.3
       1    1060    1445
Encroach Node=17673.3
       1  1000.5    1315
Encroach Node=16447.5
       1    1276  1548.3
Encroach Node=15573.2
       1    1020    1415
Encroach Node=14511
       1     915    1300
Encroach Node=13620.1
       1     970    1940
Encroach Node=12813.3
       1     682    1800
Encroach Node=11717.4
       1     445    1170
Encroach Node=11357.4
       1     510    1130
Encroach Node=11020.9
       1     430     930
Encroach Node=10636.9
       1     432     861
Encroach Node=10482.8
       1     512     920
Encroach Node=10159.3
       1     470     882
Encroach Node=9496.2
       1     800    1065
Encroach Node=8932.5
       1     765    1120
Encroach Node=8314.1
       1     510  828.33
Encroach Node=7632
       1   596.5     857
Encroach Node=6967.3
       1     760    1045
Encroach Node=6043.1
       1     845    1085
Encroach Node=5253.5
       1  702.85     985
Encroach Node=4253.2
       1     825    1175
Encroach Node=3222.2
       1     805    1284
Encroach Node=2431.9
       1     744    1164
Encroach Node=1402.3
       1   779.3  1208.9
Encroach Node=577.8
       1   785.1    1145
Computation Time Step Use Courant=        0
Computation Time Step Use Time Series=    0
Computation Time Step Count To Double=0
Computation Time Step Max Doubling=0
Computation Time Step Max Halving=0
Computation Time Step Residence Courant=0
UNET 1D Methodology=Finite Difference
Write Binary Output= 1

--- GREENBRRV2.p05 (plan) ---

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Plan Title=June2016
Program Version=4.10
Short Identifier=June2016
Geom File=g02
Flow File=f04
CheckData=True
UNET Convert EG Bridges= 0
UNET Junction Losses=0
WQ Output cell source sink nsm=0
Disregard all LS=0
Disregard all Conn=0
Disregard all Breaches=0
Disregard all Pumps=0

--- GREENBRRV2.f02 (steady flow) ---

Flow Title=Multiprofile
Program Version=5.07
Number of Profiles= 6
Profile Names=P100yr,P10yr,P25yr,P50yr,P500yr,P100yrPlus
River Rch & RM=GREENBRRV2,Main            ,19178.2
   71602   48316   57736   64747   87932   79052
Boundary for River Rch & Prof#=GREENBRRV2,Main            , 1
Up Type= 0
Dn Type= 1
Dn Known WS=1653.36
Boundary for River Rch & Prof#=GREENBRRV2,Main            , 2
Up Type= 0
Dn Type= 1
Dn Known WS=1648.5
Boundary for River Rch & Prof#=GREENBRRV2,Main            , 3
Up Type= 0
Dn Type= 1
Dn Known WS=1650.65
Boundary for River Rch & Prof#=GREENBRRV2,Main            , 4
Up Type= 0
Dn Type= 1
Dn Known WS=1652.07
Boundary for River Rch & Prof#=GREENBRRV2,Main            , 5
Up Type= 0
Dn Type= 1
Dn Known WS=1656.15
Boundary for River Rch & Prof#=GREENBRRV2,Main            , 6
Up Type= 0
Dn Type= 1
Dn Known WS=1654.68
DSS Import GetInterval= 0
DSS Import GetPeak= 0
DSS Import FillOption= 0

--- GREENBRRV2.f01 (steady flow) ---

Flow Title=Floodway
Program Version=5.07
Number of Profiles= 2
Profile Names=P100yr,Floodway
River Rch & RM=GREENBRRV2,Main            ,19178.2
   71602   71602
Boundary for River Rch & Prof#=GREENBRRV2,Main            , 1
Up Type= 0
Dn Type= 1
Dn Known WS=1653.36
Boundary for River Rch & Prof#=GREENBRRV2,Main            , 2
Up Type= 0
Dn Type= 1
Dn Known WS=1654.01
DSS Import GetInterval= 0
DSS Import GetPeak= 0
DSS Import FillOption= 0

--- GREENBRRV2.f04 (steady flow) ---

Flow Title=2016 Peak Flow
Program Version=4.10
Number of Profiles= 1
Profile Names=Peak Flow
River Rch & RM=GREENBRRV2,Main            ,19178.2
   79000
Boundary for River Rch & Prof#=GREENBRRV2,Main            , 1
Up Type= 0
Dn Type= 1
Dn Known WS=1652.1
Observed WS=GREENBRRV2      ,Main            ,19178.2 ,,1671.1
Observed WS=GREENBRRV2      ,Main            ,17673.3 ,,1669.3
Observed WS=GREENBRRV2      ,Main            ,16858.8 ,,1668.7
Observed WS=GREENBRRV2      ,Main            ,16447.5 ,,1668.4
Observed WS=GREENBRRV2      ,Main            ,15573.2 ,,1668.3
Observed WS=GREENBRRV2      ,Main            ,14511   ,,1666
Observed WS=GREENBRRV2      ,Main            ,11020.9 ,,1662.9
Observed WS=GREENBRRV2      ,Main            ,10482.8 ,,1662.8
Observed WS=GREENBRRV2      ,Main            ,9496.2  ,,1660.9
Observed WS=GREENBRRV2      ,Main            ,8314.1  ,,1659.8
Observed WS=GREENBRRV2      ,Main            ,7632    ,,1658.8
Observed WS=GREENBRRV2      ,Main            ,6967.3  ,,1658.2
Observed WS=GREENBRRV2      ,Main            ,6043.1  ,,1657.1
Observed WS=GREENBRRV2      ,Main            ,5253.5  ,,1656.6
Observed WS=GREENBRRV2      ,Main            ,4253.2  ,,1655.4
Observed WS=GREENBRRV2      ,Main            ,3222.2  ,,1655.2
Observed WS=GREENBRRV2      ,Main            ,2431.9  ,,1654.2
Observed WS=GREENBRRV2      ,Main            ,577.8   ,,1652.1
DSS Import GetInterval= 0
DSS Import GetPeak= 0
DSS Import FillOption= 0

--- GREENBRRV2.g02 (geometry) ---

Geom Title=LiDAR and Survey data
Program Version=5.03

River Reach=GREENBRRV2      ,Main
Reach XY= 30
     2128937.643      276254.605     2127631.777      274839.566
     2127076.221        274360.4     2126853.999      274117.344
      2126465.11      273568.733     2126076.221        273360.4
     2125728.999      273103.455     2125624.832      272943.733
     2125097.054      272540.955     2124534.554      271818.733
     2124208.165      271554.844     2123999.832      271443.733
     2123749.832      271374.288     2123520.665        271360.4
     2123180.388      271492.344     2122701.221      271554.844
     2122319.277      271554.844     2121867.888      271492.344
     2120145.665      270818.733     2119603.999      270540.955
     2118520.665        269735.4     2118360.943      269471.511
      2117902.61      267700.677     2117749.832      267228.455
     2117492.888        266610.4     2117263.721      266277.066
     2117055.388        266047.9     2116145.665      265145.122
     2115819.685      264541.696     2115538.603       264261.84

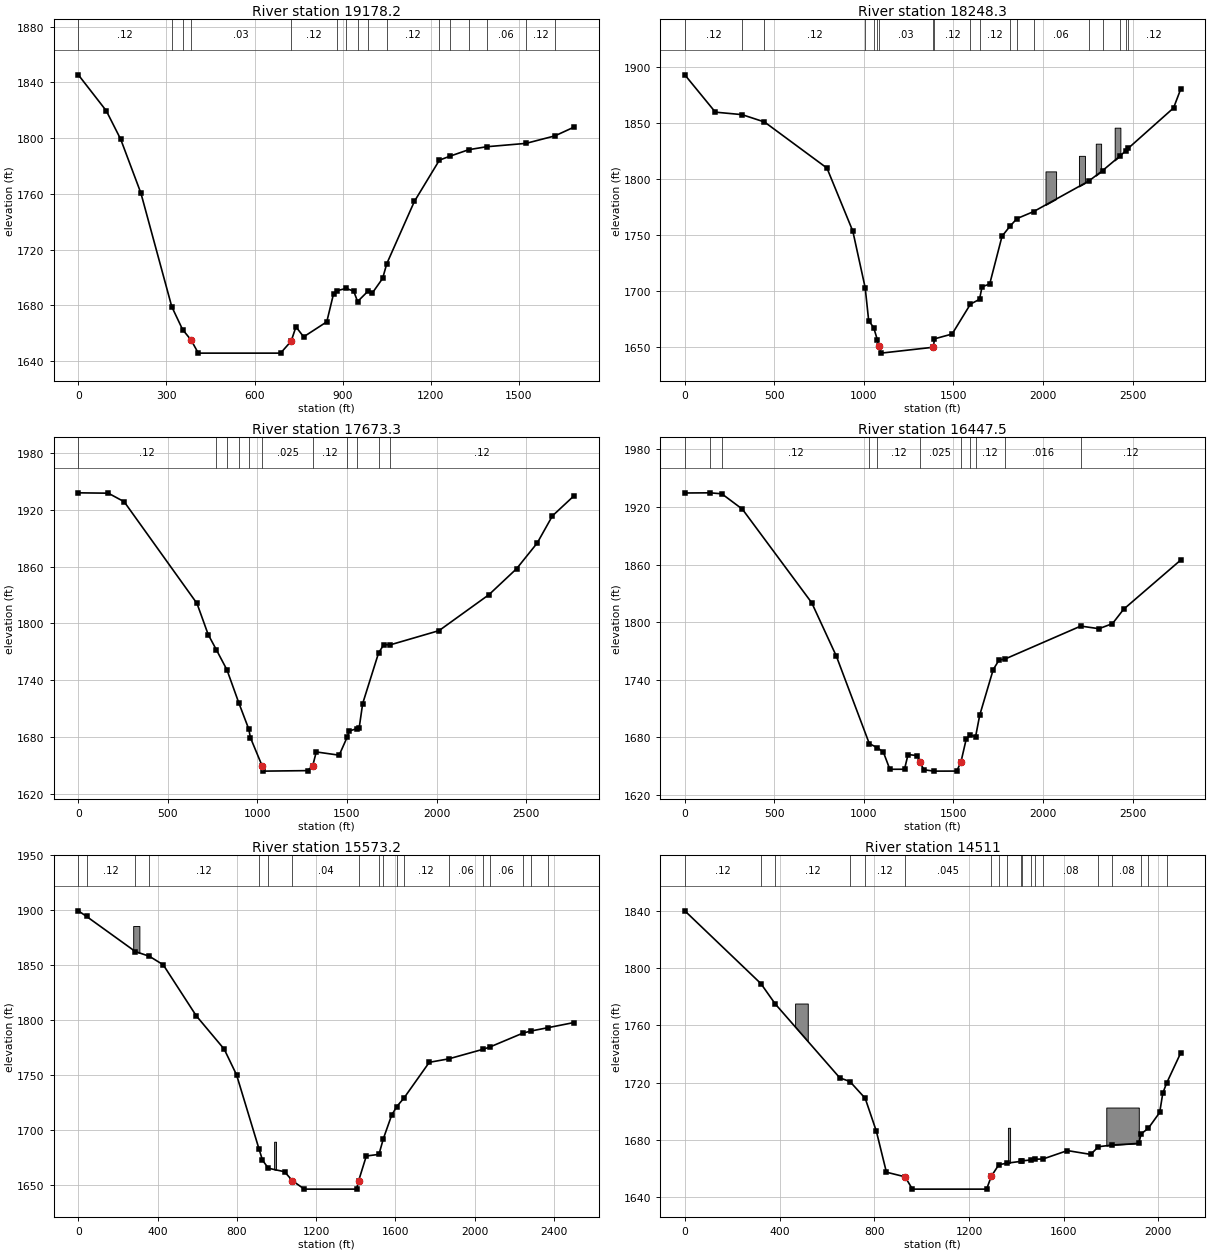
Type RM Length L Ch R = 1 ,19178.2 ,952.1,929.9,914.4
XS GIS Cut Line= 3
     2129310.994      275761.116     2128542.765      276364.414
       2128571.7      277074.773
#Sta/Elev= 30
       0 1845.48    95.1 1819.68   144.2 1799.22   213.1 1760.49     318 1679.07
   354.9 1662.61   383.5 1655.19   408.4  1645.7   688.4  1645.7   724.4 1654.25
   740.8 1664.57     767  1657.4   845.7 1668.17   868.6 1688.18   880.1 1690.48
   911.7 1692.17   937.5 1690.14   950.6 1682.72     986 1690.18   999.7 1688.54
  1035.8 1699.33  1049.9 1709.88  1143.9 1754.59  1229.1 1784.25  1265.1 1787.08
  1328.9 1791.74  1389.6 1793.85  1523.7 1796.27  1622.2 1801.65  1687.8 1807.99
#Mann= 16 ,-1 , 0
       0     .12       0     318    .016       0   354.9     .12       0
   383.5     .03       0   724.4     .12       0   880.1    .016       0
   911.7     .08       0   950.6     .12       0     986    .016       0
  1049.9     .12       0  1229.1    .016       0  1265.1     .06       0
  1328.9     .12       0  1389.6     .06       0  1523.7     .12       0
  1622.2     .06       0
Bank Sta=383.5,724.4
XS Rating Curve= 0 ,0
Exp/Cntr=0.3,0.1

Type RM Length L Ch R = 1 ,18248.3 ,575.2,575.1,575.2
Node Name=T
XS GIS Cut Line= 2
     2129144.617      274540.051     2127156.769      276467.134
#Sta/Elev= 30
       0 1893.42   170.6 1860.08   319.7 1857.86     445 1851.29   793.8 1810.12
   938.2 1753.76  1007.1 1703.35  1026.8 1673.79  1054.8 1667.62    1076 1656.26
  1082.5 1650.83  1095.9 1644.82  1387.6 1650.07  1394.1 1657.57  1492.6 1661.89
    1595  1688.6  1645.6 1692.88  1659.8 1704.06  1702.5 1706.56  1771.4 1749.25
  1815.1 1758.05  1854.7    1765  1947.6 1771.24  2255.4 1798.51  2332.8 1807.87
  2431.3 1821.07  2461.9 1825.57  2475.2 1827.67  2729.2 1863.85  2768.6 1880.48
#Mann= 19 ,-1 , 0
       0     .12       0   319.7     .06       0     445     .12       0
  1007.1    .016       0  1054.8     .12       0    1076     .03       0
  1082.5     .03       0  1387.6     .12       0  1394.1     .12       0
    1595     .08       0  1645.6     .12       0  1815.1    .016       0
  1854.7     .12       0  1947.6     .06       0  2255.4     .12       0
  2332.8     .06       0  2431.3     .12       0  2461.9     .06       0
  2475.2     .12       0
#Block Obstruct= 4 ,-1
  2014.1  2073.21807.155  2200.8  2234.3 1821.05  2294.9  2324.61831.918
  2400.4  2432.21846.203
Bank Sta=1082.5,1387.6
XS Rating Curve= 0 ,0
Exp/Cntr=0.3,0.1

Type RM Length L Ch R = 1 ,17673.3 ,1233.8,1225.8,1222.9
XS GIS Cut Line= 2
     2128704.092      274166.284     2126716.245      276093.367
#Sta/Elev= 30
       0 1937.97   167.3 1937.59   255.9 1928.56   662.6 1821.05     725 1788.25
   770.9 1772.05   829.9 1750.89   895.5 1716.29   951.3 1688.47   961.1 1679.16
  1026.8 1649.17  1033.3 1643.87 1280.02  1644.4  1308.9 1649.62  1328.5 1664.16
  1456.5 1660.71  1502.4 1680.32  1512.2 1686.27  1554.9  1688.7    1568 1689.31
  1587.7 1715.28  1676.2 1768.59  1705.8  1777.6  1741.9 1777.34  2014.1 1792.35
    2293 1830.37  2447.1 1857.76    2562 1884.84  2647.2  1913.6  2768.6 1934.99
#Mann= 11 ,-1 , 0
       0     .12       0   770.9    .016       0   829.9     .12       0
   895.5    .016       0   951.3     .12       0  1026.8    .025       0
  1308.9     .12       0  1502.4     .08       0  1554.9     .12       0
  1676.2    .016       0  1741.9     .12       0
Bank Sta=1026.8,1308.9
XS Rating Curve= 0 ,0
Exp/Cntr=0.3,0.1

Type RM Length L Ch R = 1 ,16447.5 ,891.5,874.3,868.8
XS GIS Cut Line= 2
     2127974.013      273172.774     2125986.165      275099.857
#Sta/Elev= 30
       0 1934.57     141 1934.74   206.7 1933.72   321.5 1917.72   708.6 1820.24
   846.3 1764.58    1030 1673.57    1076 1669.04  1108.8 1664.62  1144.8 1646.75
  1226.8 1646.76  1246.5 1662.11    1299 1660.95  1312.1 1654.52 1334.95 1646.24
  1390.4 1644.81 1518.13 1644.87  1541.8 1654.21  1571.3 1678.11  1594.2 1682.23
  1623.8 1680.83  1646.7 1703.02  1722.2 1750.63    1755  1760.6  1787.8 1761.57
    2211 1795.92  2312.6 1793.19  2388.1 1798.49  2450.4 1813.46  2768.6 1864.62
#Mann= 11 ,-1 , 0
       0     .12       0     141    .016       0   206.7     .12       0
    1030    .016       0    1076     .12       0  1312.1    .025       0
  1541.8     .12       0  1594.2     .08       0  1623.8     .12       0
  1787.8    .016       0    2211     .12       0
Bank Sta=1312.1,1541.8
XS Rating Curve= 0 ,0
Exp/Cntr=0.3,0.1

Type RM Length L Ch R = 1 ,15573.2 ,1108,1062.2,1008.5
XS GIS Cut Line= 4
     2127463.772      273238.546     2126810.994       273071.88
     2126112.175      273789.809     2125949.883      274599.657
#Sta/Elev= 30
       0 1899.52    41.3 1894.45     288 1862.41   358.1 1858.18   428.4 1850.38
   595.2  1803.9   735.9 1773.61   798.1  1750.3   911.7 1682.65   929.1 1672.55
   958.6  1665.2  1040.4 1662.02  1079.7 1653.88  1140.1 1646.18  1403.9 1646.18
  1413.7 1653.52    1453 1676.34  1516.7 1677.81  1539.2 1692.23  1580.6 1713.39
  1606.8 1721.38  1642.9 1729.08  1770.6 1761.61    1869 1764.78  2040.8 1773.42
  2075.1 1775.46  2242.2 1788.14  2283.7 1790.11  2367.2 1793.07  2501.6 1797.86
#Mann= 18 ,-1 , 0
       0     .06       0    41.3     .12       0     288     .08       0
   358.1     .12       0   911.7    .016       0   958.6     .12       0
  1079.7     .04       0  1413.7     .08       0  1516.7     .06       0
  1539.2     .12       0  1606.8    .016       0  1642.9     .12       0
    1869     .06       0  2040.8    .016       0  2075.1     .06       0
  2242.2    .016       0  2283.7     .06       0  2367.2     .12       0
#Block Obstruct= 2 ,-1
   276.8     3081885.705   987.8   997.41689.323
Bank Sta=1079.7,1413.7
XS Rating Curve= 0 ,0
Exp/Cntr=0.3,0.1

Type RM Length L Ch R = 1 ,14511   ,826.8,890.9,998.1
XS GIS Cut Line= 4
     2126331.827      272356.602     2125838.772       272384.38
     2125262.383      273377.435     2125241.549      273828.824
#Sta/Elev= 30
       0 1839.88   321.4 1789.09   381.9 1774.92   654.6 1723.33   697.2  1720.8
   761.8 1709.09   808.8 1686.18   851.4 1657.53   930.2 1654.29   961.3 1645.71
  1274.6 1645.71  1294.3 1654.67  1326.2 1662.72  1359.2 1663.79    1419 1665.08
  1425.2 1665.44  1461.6 1666.07  1477.3 1666.53  1513.3 1666.77  1615.8  1672.6
  1714.1 1669.94  1746.8 1675.31  1805.8 1676.48  1917.1 1677.63  1927.4 1684.35
    1957 1688.07  2005.5 1699.19  2018.6 1712.67  2034.4 1719.53  2093.9  1740.6
#Mann= 19 ,-1 , 0
       0     .12       0   321.4    .016       0   381.9     .12       0
   697.2    .016       0   761.8     .12       0   930.2    .045       0
  1294.3     .12       0  1326.2    .016       0  1359.2     .12       0
    1419     .08       0  1425.2     .12       0  1461.6     .08       0
  1477.3    .016       0  1513.3     .08       0  1746.8    .016       0
  1805.8     .08       0  1927.4    .016       0    1957     .06       0
  2034.4     .12       0
#Block Obstruct= 3 ,-1
   465.8   519.31775.211  1364.6  1373.71688.504    1780  1917.21702.633
Bank Sta=930.2,1294.3
XS Rating Curve= 0 ,0
Exp/Cntr=0.3,0.1

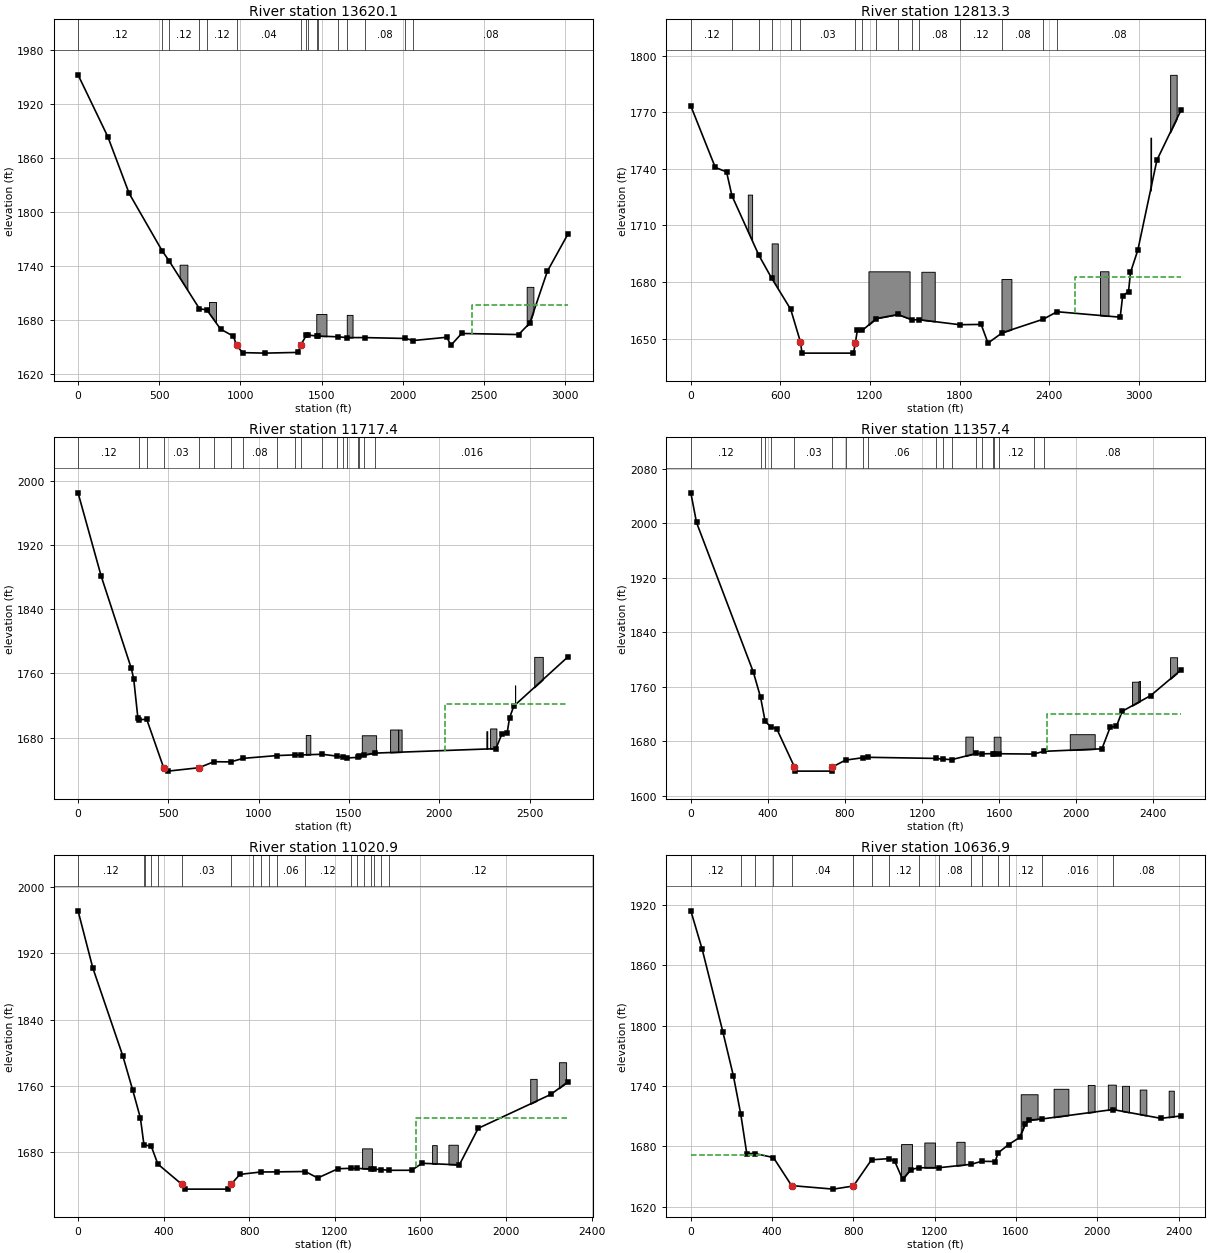
Type RM Length L Ch R = 1 ,13620.1 ,842.4,806.8,774.2
XS GIS Cut Line= 3
      2125778.44      271547.565     2124334.536      272758.112
     2123984.498      273837.394
#Sta/Elev= 30
       0 1952.02   183.5 1883.27   314.6 1820.48   518.2 1756.63   559.7 1745.89
   748.1  1692.3     793 1691.21   878.2 1669.75   956.9 1661.92   976.5 1651.84
 1013.12  1643.7  1150.5 1643.14    1356 1643.95 1371.22 1651.99  1406.8 1663.05
  1413.4 1663.18  1470.3 1662.19  1478.1 1662.11  1599.1 1661.26  1658.2 1660.39
  1765.3 1660.39  2016.9 1659.41  2064.9 1657.12  2271.2 1660.74  2297.4 1651.96
    2363 1664.97  2713.9 1663.74  2782.7 1676.57    2891 1734.05  3018.8 1775.67
#Mann= 16 ,-1 , 0
       0     .12       0   518.2    .016       0   559.7     .12       0
   748.1    .016       0     793     .12       0   976.5     .04       0
 1371.22     .12       0  1406.8     .08       0  1413.4    .016       0
  1470.3     .08       0  1478.1    .016       0  1599.1     .08       0
  1658.2     .12       0  1765.3     .08       0  2016.9    .016       0
  2064.9     .08       0
#XS Ineff= 2 , 0
                         2425.84         1696.54
Permanent Ineff=
       F       F
#Block Obstruct= 5 ,-1
   625.7   673.51741.273   806.5   849.81699.915  1467.4  1530.11686.569
  1655.3  1690.91685.591  2763.6  2804.81716.693
Bank Sta=976.5,1371.22
XS Rating Curve= 0 ,0
Exp/Cntr=0.3,0.1

Type RM Length L Ch R = 1 ,12813.3 ,1226.7,1095.9,609.3
XS GIS Cut Line= 2
     2124989.631      270974.577     2122824.979      273443.254
#Sta/Elev= 30
       0 1773.31     164 1740.73   239.4 1738.38   275.5 1725.72   455.9 1694.19
   541.2 1682.07   669.1 1665.54   734.7 1648.13   744.6 1642.31  1089.8 1642.31
  1102.1 1647.56  1115.2 1654.36    1148 1654.33  1243.1 1660.64  1387.4 1662.79
  1482.6 1659.94  1531.8 1660.02  1800.7 1657.38    1945 1657.53    1991 1647.63
  2086.1  1653.1  2361.6 1660.32  2453.6 1664.26  2876.6 1661.36    2893 1672.65
  2932.3 1674.97  2945.5 1685.08  2994.7 1696.93  3122.6 1744.66  3283.3    1771
#Mann= 16 ,-1 , 0
       0     .12       0   275.5     .08       0   455.9    .016       0
   541.2     .08       0   669.1     .12       0   734.7     .03       0
  1102.1     .12       0    1148     .08       0  1243.1    .016       0
  1387.4     .08       0  1482.6    .016       0  1531.8     .08       0
  1800.7     .12       0  2086.1     .08       0  2361.6     .12       0
  2453.6     .08       0
#XS Ineff= 2 , 0
                         2571.35         1682.82
Permanent Ineff=
       F       F
#Block Obstruct= 8 ,-1
   381.6   410.5 1726.34   541.5   582.51700.476    1190  1465.61685.671
  1544.6  1633.91685.439  2081.2  2147.6  1681.6  2741.1    27981685.708
  3078.8  3083.91756.565  3211.1  3254.91789.846
Bank Sta=734.7,1102.1
XS Rating Curve= 0 ,0
Exp/Cntr=0.3,0.1

Type RM Length L Ch R = 1 ,11717.4 ,348.9,360.1,353.5
XS GIS Cut Line= 3
     2123380.438      270898.268     2123331.827       272696.88
     2122706.827      273363.546
#Sta/Elev= 30
       0  1985.6   127.8 1881.79     295 1766.24   308.1 1753.37     331 1704.94
   337.6 1702.29   380.2 1702.81     474 1642.26   497.8 1638.08   668.6 1642.29
   752.5 1649.84   844.9 1649.58   913.3 1654.01  1101.2 1657.51  1199.1 1658.35
  1232.3 1658.26  1350.3 1659.14  1435.5 1656.78    1465 1655.39  1491.2 1654.51
  1550.2 1655.28  1556.7 1656.97  1583.2 1658.22  1643.3 1660.59  2313.5 1666.16
  2346.2 1684.37  2375.7 1686.11  2388.8 1704.44  2411.8 1719.13  2713.1 1781.01
#Mann= 19 ,-1 , 0
       0     .12       0   337.6    .016       0   380.2     .12       0
     474     .03       0   668.6     .12       0   752.5     .08       0
   844.9     .12       0   913.3     .08       0  1101.2    .016       0
  1199.1     .08       0  1232.3     .12       0  1350.3     .06       0
  1435.5     .08       0    1465     .06       0  1491.2     .12       0
  1550.2     .06       0  1556.7     .12       0  1583.2     .08       0
  1643.3    .016       0
#XS Ineff= 2 , 0
                          2031.4         1721.39
Permanent Ineff=
       F       F
#Block Obstruct= 8 ,-1
  1260.9  1285.81683.213  1570.9    16501682.851  1727.4  1771.21690.054
  1772.8  1791.21690.012  2260.3  2265.51687.972  2281.1  2315.91691.368
  2418.7  2420.21745.215  2525.4  2572.81780.742
Bank Sta=474,668.6
XS Rating Curve= 0 ,0
Exp/Cntr=0.3,0.1

Type RM Length L Ch R = 1 ,11357.4 ,311.7,336.5,386.8
XS GIS Cut Line= 3
     2123047.105       270884.38     2122970.716      272731.602
     2122581.827      273307.991
#Sta/Elev= 30
       0 2044.53    29.5    2001   324.5 1781.29   362.3 1743.98   385.8 1708.85
   415.4 1700.87   445.8 1698.14   537.6 1642.22   540.9 1635.86     731 1635.86
   734.3 1641.91   803.1 1652.05   894.9 1655.61   917.9 1656.18  1272.7 1654.52
  1311.2 1653.45  1354.9 1652.73  1480.3 1661.78  1509.2 1661.26  1568.3 1661.55
  1571.7 1661.61  1598.4  1661.4    1780  1660.9  1832.4 1664.93  2134.1 1668.61
  2176.8 1700.26  2209.6 1701.76  2239.1 1723.74  2386.7  1746.7  2544.1 1784.32
#Mann= 19 ,-1 , 0
       0     .12       0   362.3     .08       0   385.8    .016       0
   415.4     .12       0   537.6     .03       0   734.3     .12       0
   803.1     .08       0   894.9    .016       0   917.9     .06       0
  1272.7     .08       0  1311.2     .06       0  1354.9     .12       0
  1480.3     .08       0  1509.2    .016       0  1568.3     .08       0
  1571.7    .016       0  1598.4     .12       0    1780    .016       0
  1832.4     .08       0
#XS Ineff= 2 , 0
                            1850         1720.07
Permanent Ineff=
       F       F
#Block Obstruct= 6 ,-1
    2290  2323.71767.188  2324.9  2331.81768.193  1967.2  2096.61690.101
  1572.3  1607.61686.377  2487.8  2524.31803.082  1425.1    1464 1686.53
Bank Sta=537.6,734.3
XS Rating Curve= 0 ,0
Exp/Cntr=0.3,0.1

Type RM Length L Ch R = 1 ,11020.9 ,328.6,384,439.3
XS GIS Cut Line= 3
     2122804.049      270932.991     2122463.772      272745.491
     2122304.049      273162.157
#Sta/Elev= 30
       0 1971.09    68.8 1902.41   209.6 1795.89   255.5 1754.98   291.5 1721.24
   307.9 1689.24   342.7    1687   372.8 1665.84  486.04 1641.19   501.2  1635.6
     701  1635.6  714.49 1641.19   756.7  1653.4   853.6 1656.25   929.1  1656.4
  1061.8 1656.85  1120.3 1649.03  1215.2 1660.22  1274.5 1660.68  1304.4 1660.64
  1370.1 1659.76  1384.4 1659.72    1418 1659.12  1454.7 1658.29  1559.2 1658.32
  1608.3 1666.78  1781.9  1664.8  1870.2 1708.93    2209  1749.7  2290.4 1765.14
#Mann= 19 ,-1 , 0
       0     .12       0   310.5     .08       0   312.6    .016       0
   342.7     .08       0   372.8     .12       0  486.04     .03       0
  714.49     .12       0   819.6    .016       0   853.6     .08       0
   891.2     .12       0   929.1     .06       0  1061.8     .12       0
  1274.5    .016       0  1304.4     .08       0  1334.4     .12       0
  1370.1     .08       0  1384.4     .12       0    1418     .06       0
  1454.7     .12       0
#XS Ineff= 2 , 0
                          1578.8         1720.91
Permanent Ineff=
       F       F
#Block Obstruct= 5 ,-1
  1327.4  1373.41684.746  1654.6  1676.31688.635    1731  1774.7  1689.1
  2113.2  2143.21768.516  2247.3  2280.91788.579
Bank Sta=486.04,714.49
XS Rating Curve= 0 ,0
Exp/Cntr=0.5,0.3

Type RM Length L Ch R = 1 ,10636.9 ,153,154.1,146.9
BEGIN DESCRIPTION:
Merged DS Survey GRE032BU
END DESCRIPTION:
XS GIS Cut Line= 2
     2122634.779      270944.275     2121482.001      273062.331
#Sta/Elev= 30
       0 1914.26    55.7 1876.14   157.3  1794.1   209.7 1749.83     246 1711.67
   275.2 1672.85   314.7 1672.81   406.3 1668.86  495.82 1640.93   701.3 1637.42
     800 1640.54   889.2 1666.62   975.9 1667.76  1002.6 1665.45  1041.9 1647.12
  1081.2  1656.7  1120.5 1658.68  1221.7 1658.74  1378.7  1662.1  1431.2  1665.1
  1497.3 1664.89  1512.3  1673.5  1563.4 1681.73  1618.6 1688.89  1644.8 1702.26
  1664.4    1706    1730 1707.27  2076.6 1716.58  2313.2 1707.82  2411.4 1710.25
#Mann= 16 ,-1 , 0
       0     .12       0     246     .08       0   314.7    .016       0
   406.3     .12       0  495.82     .04       0     800     .12       0
   889.2    .016       0   975.9     .12       0  1120.5    .016       0
  1221.7     .08       0  1378.7    .016       0  1431.2     .08       0
  1512.3    .016       0  1563.4     .12       0    1730    .016       0
  2076.6     .08       0
#XS Ineff= 2 ,-1
       0     360  1671.3    1730  2411.4 1707.11
Permanent Ineff=
       F       F
#Block Obstruct= 10 ,-1
  1034.3  1088.41682.224    1149  1201.11683.778  1306.5    13471684.495
  1623.2    17061731.786  1785.1  1857.71737.226  1953.1  1986.6 1741.07
  2051.8    20911741.344  2121.7  2156.21740.172  2208.7  2241.31736.439
  2351.2  2376.31735.338
Bank Sta=495.82,800
XS Rating Curve= 0 ,0
Exp/Cntr=0.5,0.3

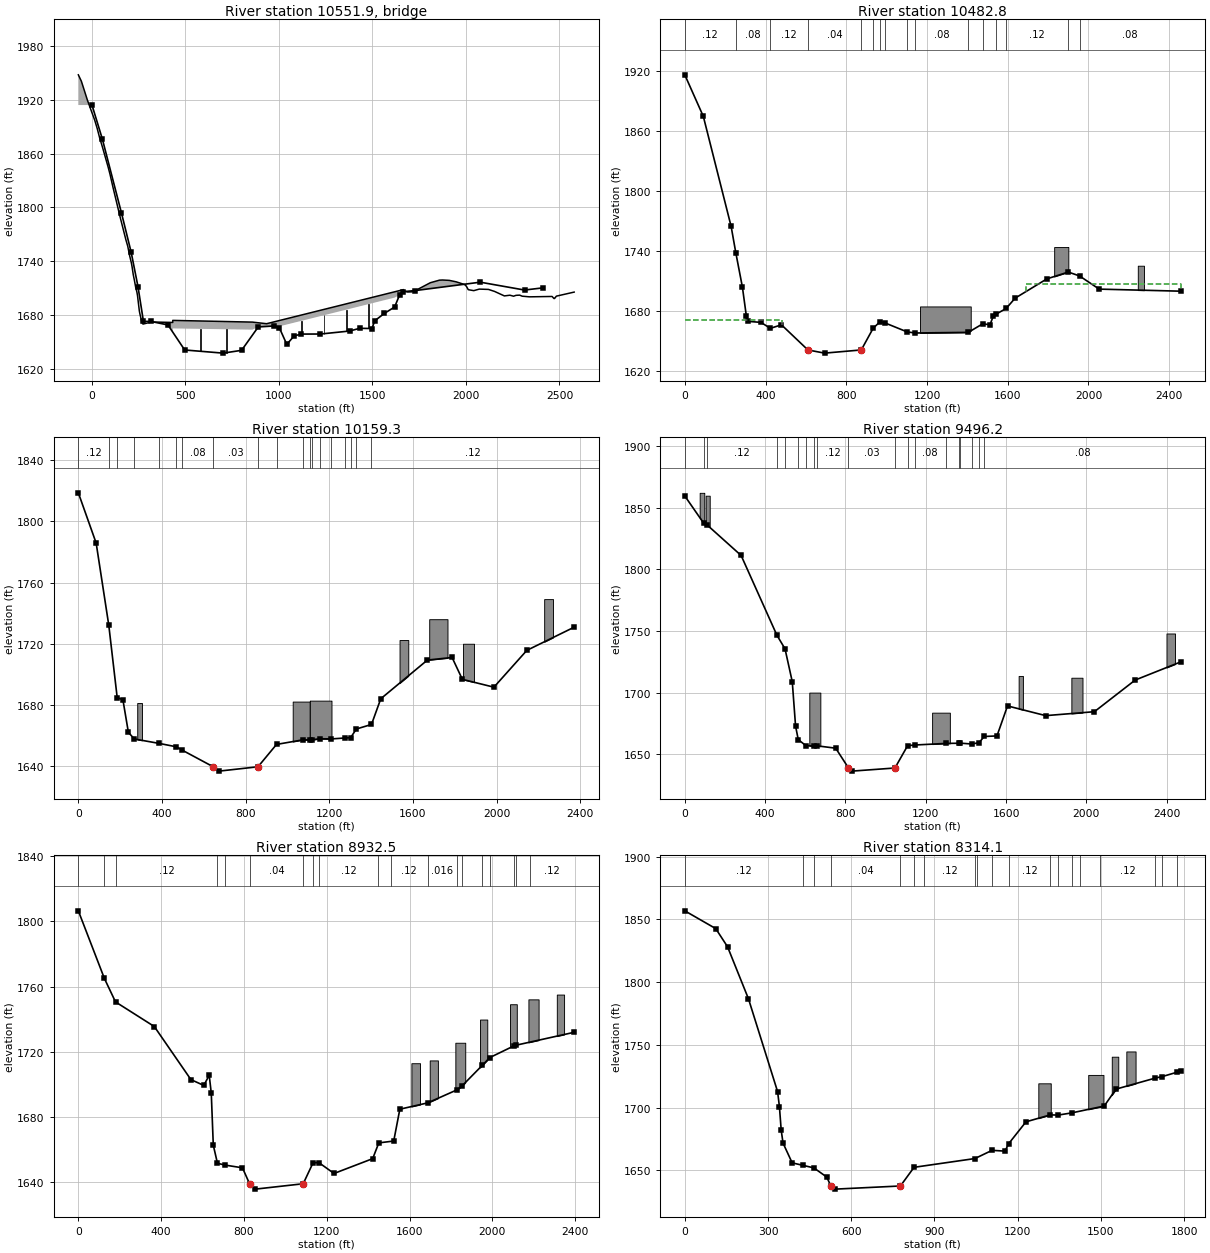
Type RM Length L Ch R = 3 ,10551.9 ,,,
BEGIN DESCRIPTION:
 GRE030RP-Bridge information is taken from the survey data. Based on recent imagery pier spacing appears to be 140' in main channel. Elongated pier with circular ends. 4 land piers approx 120' apart. Distance between last aquatic and first land pier about 400'.
END DESCRIPTION:
Bridge Culvert--1,0,-1,-1, 0
Deck Dist Width WeirC Skew NumUp NumDn MinLoCord MaxHiCord MaxSubmerge Is_Ogee
75,32.6,2.6,0, 60, 60, , , , 0, ,,,
     -73   -56.7   -24.1    15.1    28.1    41.2    54.3    86.9    96.7     113
   152.1   181.5   191.3   201.1   210.9   214.1   220.7   227.2   233.7   240.2
   243.5   253.3   256.5   266.3   269.6   272.9   318.5  431.89  431.99  857.53
   933.8  1665.5    1672  1688.3  1711.2  1737.4  1809.4  1858.5  1874.9  1910.9
  1946.9  1992.7  2002.5  2012.4  2041.8  2071.3  2120.4  2153.1  2205.5    2235
  2254.6  2267.7  2287.3  2300.4  2339.7  2460.8  2470.7  2473.9  2483.7  2578.7
 1947.98 1940.84 1919.53 1897.03 1887.99 1877.47 1868.55 1844.64 1836.75 1821.85
 1787.92 1763.77 1756.68 1746.43 1737.76 1734.18    1725 1718.34 1710.86 1705.57
 1701.55 1684.41 1681.02 1672.35 1670.54 1669.84 1672.17 1671.66 1673.96 1672.05
 1670.25  1708.3 1706.58 1705.63 1705.82 1708.08 1715.98 1718.86 1719.02  1718.6
 1717.03 1713.98 1711.99 1708.21 1707.14 1708.86 1708.51 1706.27 1701.26 1702.05
 1700.94  1701.9 1702.14 1700.97 1700.24 1700.65 1698.32  1698.4 1701.01 1705.53
                                                                                
                                                                                
                                                                 1664.98 1663.62
 1663.75  1701.8
                                                                                
                                                                                
   -13.3       3    35.6    74.8    87.8   100.9     114   146.6   156.4   172.7
   211.8   241.2     251   260.8   270.6   273.8   280.4   286.9   293.4   299.9
   303.2     313   316.2     326   329.3   332.6   352.1   368.4   378.2  502.09
  502.19  917.23  1764.4  1767.7  1793.8  1869.1  1918.2  1934.6  1970.6  2006.6
  2052.4  2062.2  2068.8  2072.1  2101.5    2131  2180.1  2212.8  2265.2  2294.7
  2314.3  2327.4    2347  2360.1  2399.4  2520.5  2530.4  2533.6  2543.4  2638.4
 1947.98 1940.84 1919.53 1897.03 1887.99 1877.47 1868.55 1844.64 1836.75 1821.85
 1787.92 1763.77 1756.68 1746.43 1737.76 1734.18    1725 1718.34 1710.86 1705.57
 1701.55 1684.41 1681.02 1672.35 1670.54 1669.84 1670.43    1672 1672.17 1671.62
 1673.92 1672.05 1705.94 1705.68 1707.74 1715.98 1718.86 1719.02  1718.6 1717.03
 1713.98 1711.99 1709.06 1708.21 1707.14 1708.86 1708.51 1706.27 1701.26 1702.05
 1700.94  1701.9 1702.14 1700.97 1700.24 1700.65 1698.32  1698.4 1701.01 1705.53
                                                                                
                                                                                
                                                                                
 1665.58 1662.81 1699.44
                                                                                
                                                                                
Pier Skew, UpSta & Num, DnSta & Num=  ,580, 2 ,640, 2 , 0 , 0 , 0 ,,
     2.5     2.5
    1635    1665
     2.5     2.5
    1635    1665
Pier Skew, UpSta & Num, DnSta & Num=  ,720, 2 ,780, 2 , 0 , 0 , 0 ,,
     2.5     2.5
    1635    1665
     2.5     2.5
    1635    1665
Pier Skew, UpSta & Num, DnSta & Num=  ,1120, 2 ,1180, 2 , 0 , 0 , 0 ,,
     2.5     2.5
    1650    1675
     2.5     2.5
    1650    1675
Pier Skew, UpSta & Num, DnSta & Num=  ,1240, 2 ,1300, 2 , 0 , 0 , 0 ,,
     2.5     2.5
    1650    1682
     2.5     2.5
    1650    1682
Pier Skew, UpSta & Num, DnSta & Num=  ,1360, 2 ,1420, 2 , 0 , 0 , 0 ,,
     2.5     2.5
    1650    1688
     2.5     2.5
    1650    1688
Pier Skew, UpSta & Num, DnSta & Num=  ,1480, 2 ,1540, 2 , 0 , 0 , 0 ,,
     2.5     2.5
    1650    1694
     2.5     2.5
    1650    1694
BR Coef=-1 , 1 , 0 ,, 0 ,,,0.8,-1,1.33,0,
WSPro=,,,, 1 ,,,, 0 ,,,, 0 ,,,,-1 ,-1 ,-1 , 0 , 0 , 0 , 0 , 0
BR U #Sta/Elev= 30
       0 1914.26    55.7 1876.14   157.3  1794.1   209.7 1749.83     246 1711.67
   275.2 1672.85   314.7 1672.81   406.3 1668.86  495.82 1640.93   701.3 1637.42
     800 1640.54   889.2 1666.62   975.9 1667.76  1002.6 1665.45  1041.9 1647.12
  1081.2  1656.7  1120.5 1658.68  1221.7 1658.74  1378.7  1662.1  1431.2  1665.1
  1497.3 1664.89  1512.3  1673.5  1563.4 1681.73  1618.6 1688.89  1644.8 1702.26
  1664.4    1706    1730 1707.27  2076.6 1716.58  2313.2 1707.82  2411.4 1710.25
BR U #Mann= 16
       0     .12     246     .08   314.7    .016   406.3     .12  495.82    .039
     800     .12   889.2    .016   975.9     .12  1120.5    .016  1221.7     .08
  1378.7    .016  1431.2     .08  1512.3    .016  1563.4     .12    1730    .016
  2076.6     .08
BR D #Sta/Elev= 30
       0 1915.69    91.8 1874.16   229.6 1764.21   252.6 1738.07   285.4 1703.61
     305 1674.72   311.6 1669.44   377.2 1668.38   423.9 1662.45   478.9 1665.96
     610 1640.84   692.5 1637.67   874.4 1640.85   933.6 1662.65   967.5 1669.03
   993.4 1667.72    1102 1658.84    1143 1657.78  1404.3  1658.4  1475.7 1666.91
    1512 1666.07  1528.4 1674.58  1544.2 1676.81    1592 1682.26  1636.6 1692.58
  1794.1 1711.86    1900 1718.66  1955.6  1714.8  2053.2 1701.62  2456.6 1699.55
BR D #Mann= 16
       0     .12   252.6     .08   423.9     .12     610    .039   874.4     .12
   933.6     .08   967.5    .016   993.4     .08    1102    .016    1143     .08
  1404.3    .016  1475.7     .08  1544.2    .016    1592     .12    1900    .016
  1955.6     .08
BC Design=,, 0 ,, 0 ,,0,,,,
BC HTab HWMax=0
BC HTab TWMax=0
BC HTab MaxFlow=0
BC Use User HTab Curves=0
BC User HTab FreeFlow(D)= 0

Type RM Length L Ch R = 1 ,10482.8 ,321.5,323.5,320.8
BEGIN DESCRIPTION:
Merged US Survey GRE028BD
END DESCRIPTION:
XS GIS Cut Line= 2
     2122526.272      270870.491     2121317.938       273009.38
#Sta/Elev= 30
       0 1915.69    91.8 1874.16   229.6 1764.21   252.6 1738.07   285.4 1703.61
     305 1674.72   311.6 1669.44   377.2 1668.38   423.9 1662.45   478.9 1665.96
     610 1640.84   692.5 1637.67   874.4 1640.85   933.6 1662.65   967.5 1669.03
   993.4 1667.72    1102 1658.84    1143 1657.78  1404.3  1658.4  1475.7 1666.91
    1512 1666.07  1528.4 1674.58  1544.2 1676.81    1592 1682.26  1636.6 1692.58
  1794.1 1711.86    1900 1718.66  1955.6  1714.8  2053.2 1701.62  2456.6 1699.55
#Mann= 16 ,-1 , 0
       0     .12       0   252.6     .08       0   423.9     .12       0
     610     .04       0   874.4     .12       0   933.6     .08       0
   967.5    .016       0   993.4     .08       0    1102    .016       0
    1143     .08       0  1404.3    .016       0  1475.7     .08       0
  1544.2    .016       0    1592     .12       0    1900    .016       0
  1955.6     .08       0
#XS Ineff= 2 ,-1
       0     480    1671    1690  2456.6    1707
Permanent Ineff=
       F       F
#Block Obstruct= 3 ,-1
  1165.5  1416.71684.318    1830  1900.21743.635  2244.4    22751724.992
Bank Sta=610,874.4
XS Rating Curve= 0 ,0
Exp/Cntr=0.5,0.3

Type RM Length L Ch R = 1 ,10159.3 ,687.5,663,647.3
Node Name=S
XS GIS Cut Line= 2
     2122185.994      270828.824     2121054.049      272912.157
#Sta/Elev= 30
       0 1818.55    85.3 1785.72   145.7 1732.04   185.8  1684.9   213.2 1683.46
   239.4 1662.19   267.9 1657.88   387.6 1654.97   468.2 1652.79   497.6 1650.53
   644.2  1639.8   672.3  1636.9   859.2 1639.74   947.7 1654.33    1072 1657.28
    1108 1657.32  1116.4 1657.34    1155 1658.04  1210.2 1657.92    1275 1658.53
  1301.9 1658.73  1329.7 1664.41  1401.9 1667.36  1446.2 1684.13  1669.2 1709.39
  1787.3 1711.07  1836.4  1696.8  1987.3 1691.69  2144.7 1715.72    2371 1730.85
#Mann= 19 ,-1 , 0
       0     .12       0   145.7     .08       0   185.8    .016       0
   267.9     .12       0   387.6     .06       0   468.2     .12       0
   497.6     .08       0   644.2     .03       0   859.2     .12       0
   947.7    .016       0    1072     .08       0    1108     .12       0
  1116.4    .016       0    1155     .08       0  1210.2    .016       0
    1275     .08       0  1301.9     .12       0  1329.7     .08       0
  1401.9     .12       0
#Block Obstruct= 7 ,-1
   281.6   304.31681.354  1025.1  1106.51682.297    1107  1210.61682.918
    1536  1577.7 1722.46  1677.9  1765.31736.069  1839.5  1892.21720.047
  2227.6  2269.91749.176
Bank Sta=644.2,859.2
XS Rating Curve= 0 ,0
Exp/Cntr=0.3,0.1

Type RM Length L Ch R = 1 ,9496.2  ,553,563.7,571.6
XS GIS Cut Line= 3
     2121797.105      270557.991     2121387.383      270794.102
     2120665.161      272655.213
#Sta/Elev= 30
       0 1859.69    94.6 1837.42   109.2 1836.42   280.5 1811.36   458.8 1746.56
   499.1 1735.54   535.2 1708.84   551.6  1672.8     565 1661.84   602.9 1656.94
   645.6  1656.6     657  1656.8   751.5 1654.86   815.1 1638.79   832.3 1636.23
  1046.5 1638.77  1109.8 1656.93  1144.9 1657.44  1299.9 1658.72  1363.3 1658.88
  1371.5 1658.96  1430.1 1658.24  1466.1 1659.41  1490.7 1664.36  1554.6 1664.82
  1607.1 1689.18  1797.2  1681.3  2039.8 1684.49    2243  1710.2  2469.2  1724.9
#Mann= 19 ,-1 , 0
       0     .12       0    94.6     .08       0   109.2     .12       0
   458.8    .016       0   499.1     .12       0     565    .016       0
   602.9     .12       0   645.6     .08       0     657     .12       0
   815.1     .03       0  1046.5     .12       0  1109.8    .016       0
  1144.9     .08       0  1299.9    .016       0  1363.3     .12       0
  1371.5    .016       0  1430.1     .08       0  1466.1     .12       0
  1490.7     .08       0
#Block Obstruct= 7 ,-1
    74.1      971862.232   103.9   124.11859.901     620     675    1700
  1231.6    13201683.717  1662.5  1683.81713.529  1925.1  1980.51712.079
  2398.8  2441.11748.007
Bank Sta=815.1,1046.5
XS Rating Curve= 0 ,0
Exp/Cntr=0.3,0.1

Type RM Length L Ch R = 1 ,8932.5  ,571.2,618.4,639.1
XS GIS Cut Line= 3
     2121449.883      270655.213     2120845.716      270703.824
     2120081.827       272321.88
#Sta/Elev= 30
       0 1806.47   125.9 1764.96   179.6 1750.57     367 1735.47   543.9 1702.88
   606.1 1699.31   632.3 1705.56   642.2 1694.66     652 1662.65   672.1 1651.52
   709.2 1650.41   792.9 1648.74   827.2 1638.96   855.4 1635.66  1086.4 1638.96
  1133.9 1651.82  1161.8 1651.96  1235.3 1645.27  1422.1 1654.37  1451.6 1664.04
  1523.7 1665.18  1553.2 1684.71  1687.8  1688.6  1828.5 1696.54  1852.5 1698.84
  1951.6 1711.65  1987.5 1716.38  2105.3 1723.64  2113.8 1723.97  2395.4 1731.92
#Mann= 19 ,-1 , 0
       0     .12       0   125.9    .016       0   179.6     .12       0
   672.1    .016       0   709.2     .12       0   827.2     .04       0
  1086.4     .12       0  1133.9    .016       0  1161.8     .12       0
  1448.2     .08       0  1509.2     .12       0  1687.8    .016       0
  1828.5     .08       0  1852.5    .016       0  1951.6     .12       0
  1987.5    .016       0  2105.3     .08       0  2113.8    .016       0
    2181     .12       0
#Block Obstruct= 7 ,-1
  1609.1  1650.81712.941  1697.6  1737.11714.657  1821.4  1869.21725.505
  1940.6  1975.61739.747  2085.6  2118.31749.146  2174.4  2223.61752.134
  2311.6  2346.7 1755.07
Bank Sta=827.2,1086.4
XS Rating Curve= 0 ,0
Exp/Cntr=0.3,0.1

Type RM Length L Ch R = 1 ,8314.1  ,695.1,682.1,681.2
XS GIS Cut Line= 2
     2120567.938      270280.213     2119401.272       271634.38
#Sta/Elev= 30
       0  1856.9   111.5 1842.73   154.1 1828.25   229.6 1786.71   334.5 1712.78
   341.1 1700.78   347.6  1681.8   354.2 1671.71     387 1655.99     425 1654.03
   465.3 1651.97   511.6 1644.66   526.7 1637.54   542.4 1635.03   777.3 1637.54
   826.4 1652.42  1045.8 1659.41  1107.7 1665.96  1154.4 1665.32  1167.5 1671.25
  1229.9 1688.69  1317.5 1694.22    1346 1694.06  1395.1 1695.82  1511.9 1701.28
  1554.6 1714.77  1696.6  1723.6  1721.3 1724.77    1775 1728.27  1787.4 1729.09
#Mann= 19 ,-1 , 0
       0     .12       0     425    .016       0   465.3     .12       0
   526.7     .04       0   777.3     .12       0   826.4    .016       0
   861.9     .12       0  1045.8     .06       0    1054     .12       0
  1107.7     .08       0  1167.5     .12       0  1317.5    .016       0
    1346     .06       0  1395.1    .016       0  1422.9     .08       0
  1496.2     .12       0  1696.6     .06       0  1721.3     .12       0
    1775     .06       0
#Block Obstruct= 4 ,-1
  1274.4  1319.21719.383  1454.3  1509.21726.078  1539.2  1562.61740.598
  1591.7    16251744.785
Bank Sta=526.7,777.3
XS Rating Curve= 0 ,0
Exp/Cntr=0.3,0.1