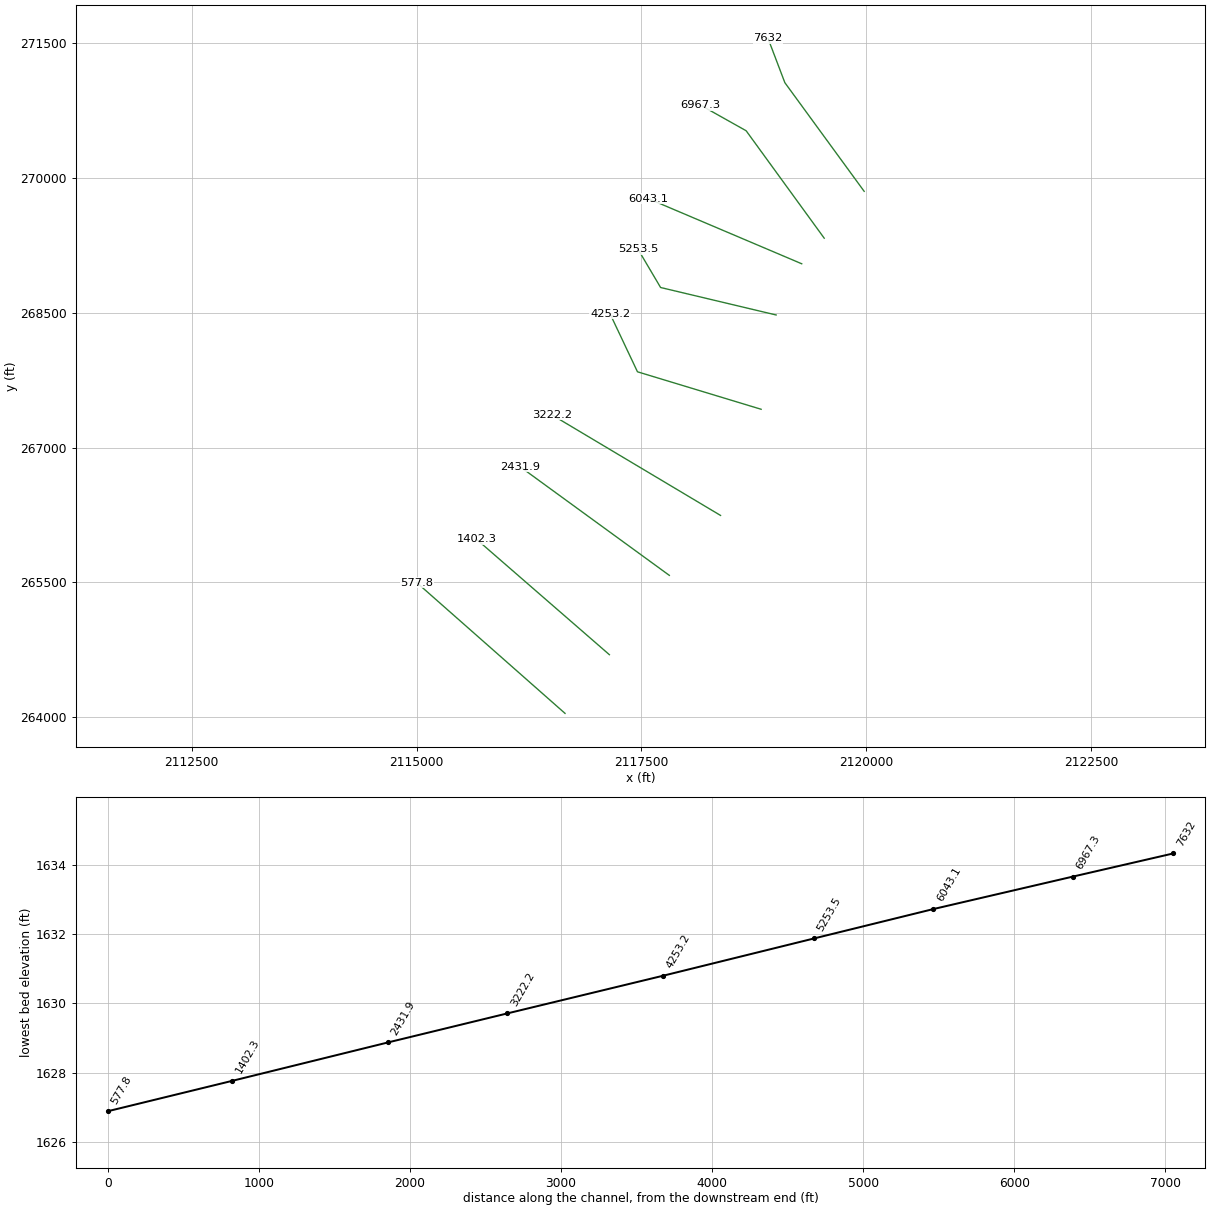
HEC-RAS study GREENBRRV2.prj: GREENBRRV2

--- GREENBRRV2.g02 (geometry) --- (continued)

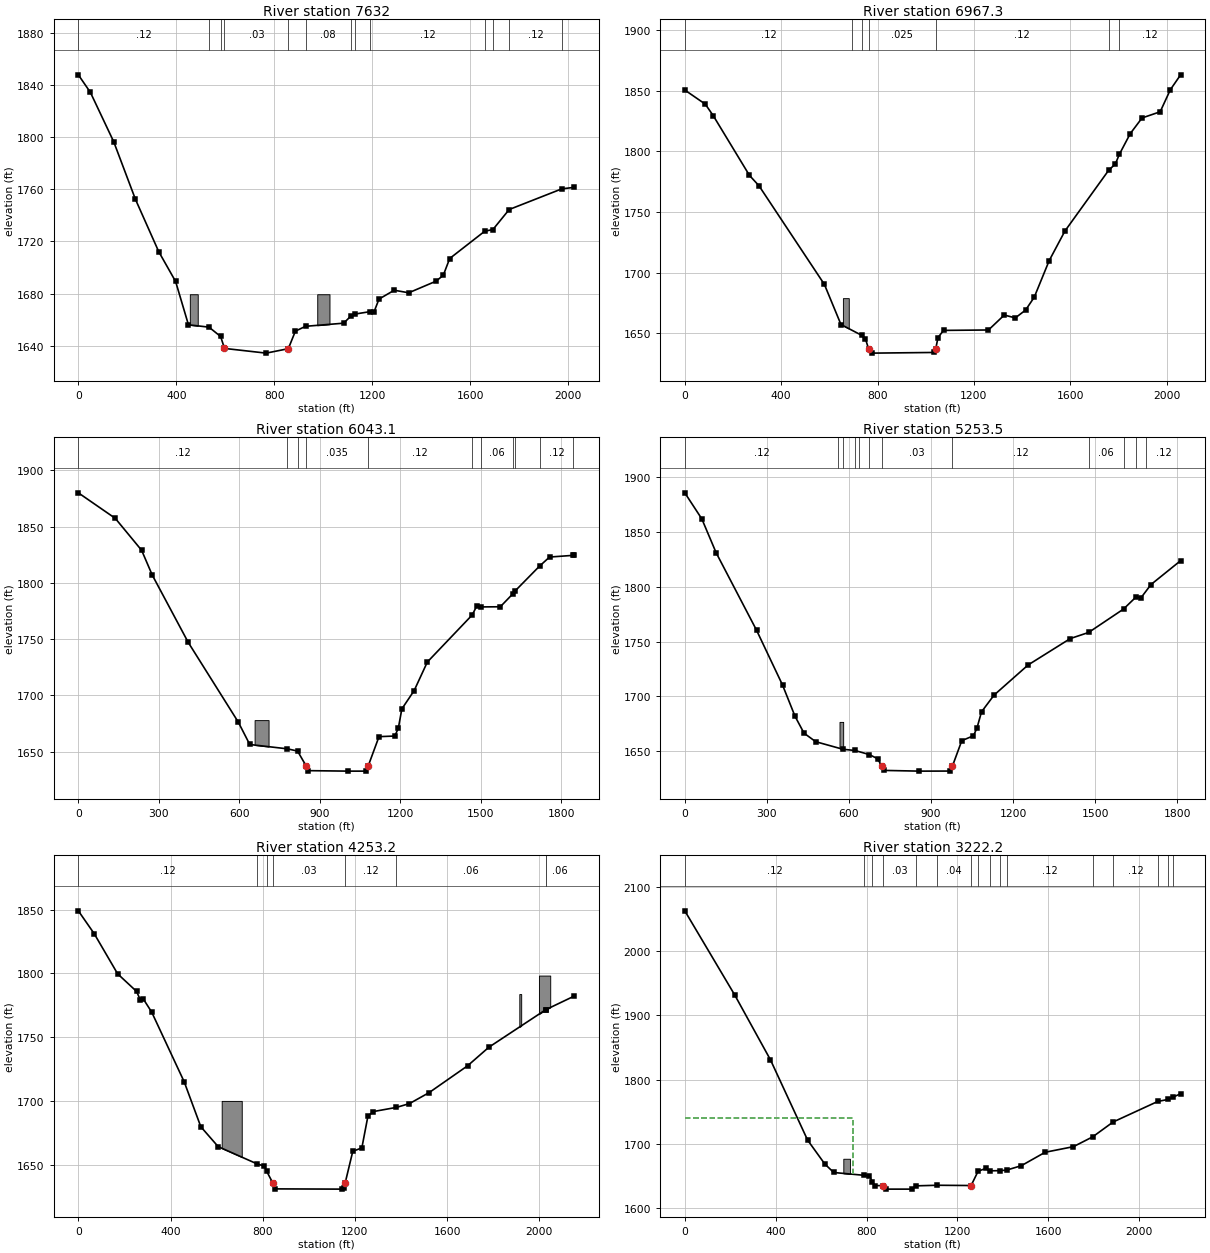
Type RM Length L Ch R = 1 ,7632    ,665,664.7,666.2
XS GIS Cut Line= 3
     2119977.661      269849.657     2119095.716      271057.991
     2118908.216      271551.046
#Sta/Elev= 30
       0 1847.77    49.2 1834.32   144.4 1796.46   232.9 1752.36   328.1 1712.17
     397 1689.28   449.4 1656.06   533.2 1654.27   580.7  1647.1   596.5 1637.95
   766.5 1634.34     857 1637.75   885.8 1651.19   927.2 1654.91  1082.6  1657.3
    1112 1662.69  1130.9 1664.36  1192.3  1666.2  1207.3 1666.23    1227 1675.79
  1289.3 1682.58  1348.3 1680.61  1459.9 1689.52  1489.4 1694.05  1515.6 1706.91
  1658.7 1727.86  1691.8 1729.09  1758.4 1744.48  1973.4 1760.35  2023.5 1761.46
#Mann= 13 ,-1 , 0
       0     .12       0   533.2    .016       0   580.7     .12       0
   596.5     .03       0     857     .12       0   927.2     .08       0
    1112     .12       0  1130.9     .08       0  1192.3     .12       0
  1658.7    .016       0  1691.8     .06       0  1758.4     .12       0
  1973.4    .016       0
#Block Obstruct= 2 ,-1
     455   487.3  1679.5     975    1025  1679.5
Bank Sta=596.5,857
XS Rating Curve= 0 ,0
Exp/Cntr=0.3,0.1

Type RM Length L Ch R = 1 ,6967.3  ,810.1,924.3,981.8
XS GIS Cut Line= 3
     2119533.216      269328.824     2118665.161      270523.268
     2118158.216      270807.991
#Sta/Elev= 30
       0 1850.51    85.1 1838.86   117.9 1829.43   268.5 1780.12   307.8 1771.63
   579.5 1690.27   648.2 1657.24   735.7  1648.2   749.7 1645.44   763.5 1636.84
   778.6 1633.67  1034.4 1634.22  1041.1 1636.82  1050.9 1646.48  1073.9 1652.41
  1260.5 1652.74    1326 1665.06  1371.8  1662.7  1414.4 1669.13  1450.4 1679.75
  1512.5 1709.93  1577.8 1734.31  1759.8  1784.5  1786.9  1789.5  1803.9 1797.61
  1848.9 1814.58  1897.9  1827.5  1973.1 1832.58  2015.5 1850.83    2058 1863.04
#Mann= 7 ,-1 , 0
       0     .12       0   695.6    .016       0   735.7     .12       0
   763.5    .025       0  1041.1     .12       0  1759.8    .016       0
  1803.9     .12       0
#Block Obstruct= 1 ,-1
   656.3   680.61678.979
Bank Sta=763.5,1041.1
XS Rating Curve= 0 ,0
Exp/Cntr=0.3,0.1

Type RM Length L Ch R = 1 ,6043.1  ,756.5,789.6,802.6
Node Name=R
XS GIS Cut Line= 2
     2119283.216      269044.102     2117581.827      269766.324
#Sta/Elev= 30
       0 1880.09   137.6 1857.43     236    1829   275.3 1807.12   409.6 1747.18
   596.4 1676.25     639 1656.41   779.2 1652.55   817.2 1650.56   849.6 1637.17
   855.6 1633.16  1005.3 1632.73  1071.6 1632.73  1080.4  1637.2  1120.8 1663.37
  1179.8 1663.92  1192.9 1670.96    1206 1688.04  1251.9 1704.34    1301  1729.7
  1468.5  1771.6  1484.6 1779.24  1500.6 1778.68    1573 1778.82  1619.6 1790.28
  1627.3 1792.66  1719.2 1814.94  1756.6 1823.01  1845.5 1824.53  1848.3 1824.49
#Mann= 11 ,-1 , 0
       0     .12       0   779.2    .016       0   817.2     .12       0
   849.6    .035       0  1080.4     .12       0  1468.5     .08       0
  1500.6     .06       0  1619.6     .08       0  1627.3     .06       0
  1719.2     .12       0  1845.5    .016       0
#Block Obstruct= 1 ,-1
   657.1   709.11678.068
Bank Sta=849.6,1080.4
XS Rating Curve= 0 ,0
Exp/Cntr=0.3,0.1

Type RM Length L Ch R = 1 ,5253.5  ,1009.5,1000.3,993.6
XS GIS Cut Line= 3
     2118998.494      268474.657     2117713.772      268780.213
     2117463.772      269203.824
#Sta/Elev= 30
       0 1885.88    62.3 1862.06   114.7 1831.11   262.2 1760.52   357.2 1710.49
     403 1681.88   435.8 1666.54   478.4 1658.75   578.2 1651.82   621.5 1650.74
   674.4 1647.01   704.5 1643.22   720.1 1636.46   728.9 1632.53   857.1 1631.88
     968 1631.94   978.2 1636.42  1012.5 1659.69  1055.1 1664.15  1068.2 1671.38
  1084.6 1686.01  1130.5 1701.28    1255 1728.79  1409.1 1752.87    1476 1758.43
  1603.6 1779.78  1648.5  1790.6  1668.2 1790.31  1704.2  1802.2  1812.4 1823.97
#Mann= 12 ,-1 , 0
       0     .12       0   559.9     .06       0   578.2     .12       0
   621.5     .06       0   638.4    .016       0   674.4     .12       0
   720.1     .03       0   978.2     .12       0    1476     .06       0
  1603.6     .12       0  1650.1    .016       0  1686.3     .12       0
#Block Obstruct= 1 ,-1
   565.5   578.91676.809
Bank Sta=720.1,978.2
XS Rating Curve= 0 ,0
Exp/Cntr=0.3,0.1

Type RM Length L Ch R = 1 ,4253.2  ,1058.1,1031,971.9
XS GIS Cut Line= 3
     2118831.827      267426.046     2117456.827      267842.713
     2117151.272      268488.546
#Sta/Elev= 30
       0  1849.1    68.9 1831.16   170.6 1799.66   252.6 1785.89     269  1779.2
   282.1  1779.9   318.2 1769.68   459.2 1715.03   531.4 1679.74   606.8 1664.12
   775.9 1650.57   806.9 1648.85   817.2 1644.78     843 1635.87   855.4 1630.99
  1143.8  1630.8  1150.6  1631.5  1157.9  1635.8  1190.7 1660.45  1230.1 1663.16
  1256.3 1687.94  1279.3 1691.62  1380.2 1694.92  1436.7  1697.9    1522 1706.51
  1689.1 1727.58  1780.9 1742.08  2027.5 1771.49  2029.2 1771.66  2151.2  1782.2
#Mann= 8 ,-1 , 0
       0     .12       0   775.9    .016       0   817.2     .12       0
     843     .03       0  1157.9     .12       0  1380.2     .06       0
  2027.5     .12       0  2029.2     .06       0
#Block Obstruct= 3 ,-1
     622     709    1700  1913.3  1921.41783.808  1998.4  2047.41798.308
Bank Sta=843,1157.9
XS Rating Curve= 0 ,0
Exp/Cntr=0.3,0.1

Type RM Length L Ch R = 1 ,3222.2  ,801.6,790.2,764.5
XS GIS Cut Line= 2
     2118380.438      266245.491     2116505.438      267363.546
#Sta/Elev= 30
       0 2062.53   219.6 1931.78     377 1830.91   540.8 1705.87   616.2  1668.9
   655.6 1655.58   789.7 1651.19   812.9 1650.56     826 1640.66   839.1 1635.15
   871.9 1635.24   886.1 1629.71   998.9 1629.71  1019.4 1634.83  1111.2 1635.72
 1260.54 1635.31  1291.3 1657.51  1324.2 1661.83    1342 1658.18  1387.1 1658.44
  1417.3 1659.36  1481.6 1666.14  1586.5 1687.04    1711 1695.75  1795.9 1711.03
  1885.6 1734.09    2082 1766.02  2126.4 1769.13  2148.6 1772.62    2183 1778.04
#Mann= 16 ,-1 , 0
       0     .12       0   789.7    .016       0     826     .12       0
   871.9     .03       0  1019.4     .08       0  1111.2     .04       0
 1260.54     .12       0  1291.3     .08       0    1342     .12       0
  1387.1     .06       0  1417.3     .12       0  1795.9     .06       0
  1885.6     .12       0    2082    .016       0  2126.4     .12       0
  2148.6    .016       0
#XS Ineff= 2 , 0
           739.3 1740.38
Permanent Ineff=
       F       F
#Block Obstruct= 1 ,-1
   697.9     7271676.949
Bank Sta=871.9,1260.54
XS Rating Curve= 0 ,0
Exp/Cntr=0.3,0.1

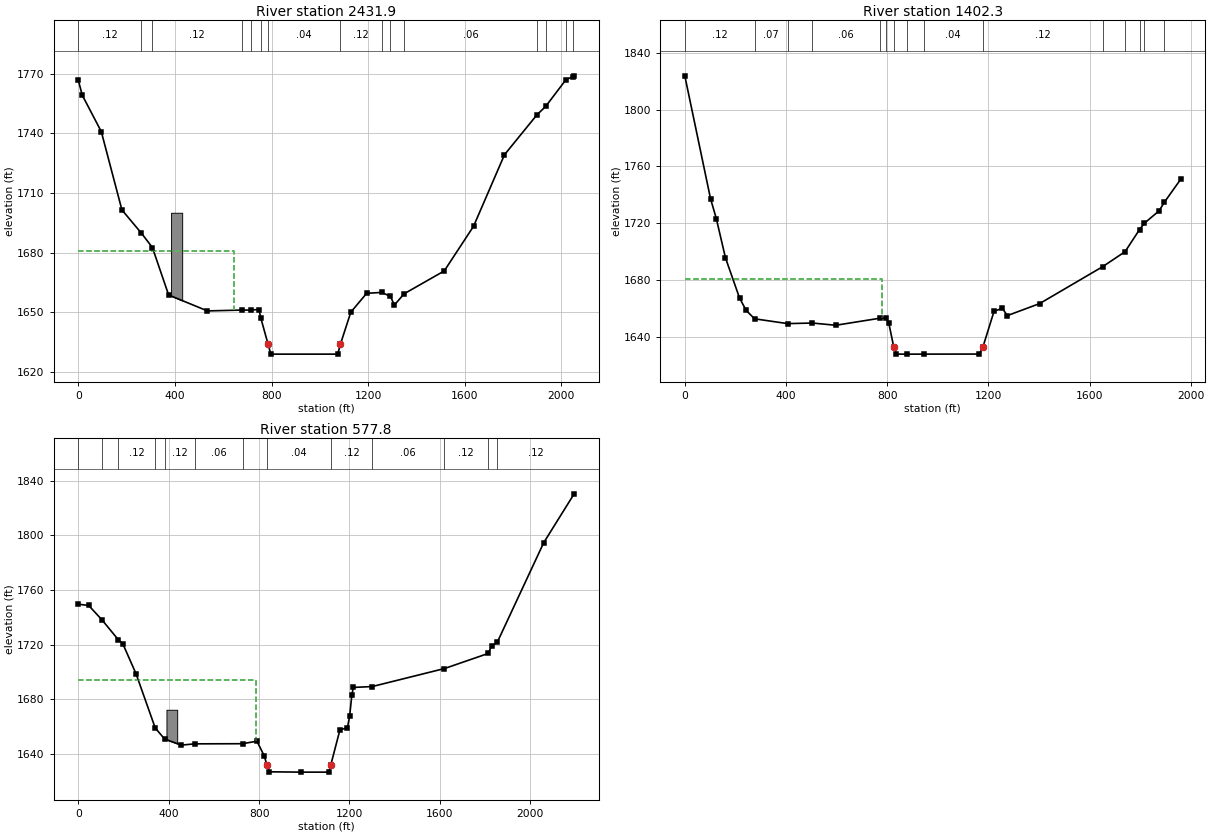
Type RM Length L Ch R = 1 ,2431.9  ,1059.8,1029.6,1007.5
XS GIS Cut Line= 2
     2117810.994      265578.824     2116151.272      266787.157
#Sta/Elev= 30
       0  1766.6    16.4 1759.11    95.1 1740.82   180.4 1701.44   261.4 1689.69
   306.7  1682.5   373.9 1658.63   534.6 1650.61   676.3 1651.03   713.6 1651.04
   747.7 1651.32     756 1646.86   785.3 1633.98     797 1628.87    1074 1628.87
  1085.5 1633.97  1128.2 1649.97  1193.8 1659.46  1255.4 1659.92  1292.4 1657.94
  1308.5 1653.52  1348.7 1659.21  1515.1 1670.73  1636.5 1693.21  1764.4 1729.17
  1899.3 1749.33  1934.8 1753.46  2019.6 1767.03  2049.1 1768.52    2053 1768.89
#Mann= 15 ,-1 , 0
       0     .12       0   261.4    .016       0   306.7     .12       0
   676.3     .06       0   713.6    .016       0     756     .12       0
   785.3     .04       0  1085.5     .12       0  1255.4    .016       0
  1292.4     .12       0  1348.7     .06       0  1899.3    .016       0
  1934.8     .12       0  2019.6    .016       0  2049.1     .12       0
#XS Ineff= 2 , 0
           643.3 1680.98
Permanent Ineff=
       F       F
#Block Obstruct= 1 ,-1
     384     430    1700
Bank Sta=785.3,1085.5
XS Rating Curve= 0 ,0
Exp/Cntr=0.3,0.1

Type RM Length L Ch R = 1 ,1402.3  ,814.1,824.6,812.1
XS GIS Cut Line= 2
     2117144.327       264696.88     2115665.161      265981.602
#Sta/Elev= 30
       0 1823.77   101.6 1737.28   124.5 1723.24   160.5  1695.7   216.2 1667.34
   242.4 1658.56   275.7 1652.64   406.2 1649.25   504.5 1649.66   596.3 1648.09
   769.9 1653.02   795.9 1653.11     806 1649.69   825.6 1632.79   835.4 1627.76
   879.5 1627.76   943.6 1627.76  1164.2 1627.81  1178.1 1632.87    1222 1657.95
  1254.8 1660.03  1274.5  1654.9  1402.2 1663.37    1651 1689.34  1739.7 1699.92
  1796.7 1715.46    1816 1719.97    1874 1728.66  1895.3 1734.85  1959.2 1750.84
#Mann= 15 ,-1 , 0
       0     .12       0   275.7     .07       0   406.2     .12       0
   504.5     .06       0   769.9    .016       0   795.9     .12       0
   825.6     .04       0   879.5     .08       0   943.6     .04       0
  1178.1     .12       0    1651     .06       0  1739.7    .016       0
  1796.7     .12       0    1816    .016       0  1895.3     .12       0
#XS Ineff= 2 , 0
           779.3 1680.94
Permanent Ineff=
       F       F
Bank Sta=825.6,1178.1
XS Rating Curve= 0 ,0
Exp/Cntr=0.3,0.1

Type RM Length L Ch R = 1 ,577.8   ,658.1,577.8,595.9
XS GIS Cut Line= 2
     2116651.272      264044.102     2115005.438      265495.491
#Sta/Elev= 30
       0 1749.64    45.9 1748.68   104.8 1738.14   176.5 1723.73   196.8 1720.71
   255.8 1698.61   340.2 1659.18   381.9 1651.07   455.9 1646.62   514.9 1647.55
   726.6 1647.65   790.5  1649.5   823.3 1638.57   834.4 1632.05   844.6 1627.12
   984.6 1626.88  1108.7 1626.88  1117.1 1632.02  1157.9 1657.87  1190.7 1659.26
  1200.5 1667.54  1210.4 1683.05  1216.9  1688.8  1300.4 1689.42  1620.4 1702.59
  1813.6  1713.6  1830.3 1719.34    1854 1721.75  2059.9 1794.65  2194.4 1830.29
#Mann= 13 ,-1 , 0
       0     .12       0   104.8     .06       0   176.5     .12       0
   340.2    .016       0   381.9     .12       0   514.9     .06       0
   726.6     .12       0   834.4     .04       0  1117.1     .12       0
  1300.4     .06       0  1620.4     .12       0  1813.6    .016       0
    1854     .12       0
#XS Ineff= 2 , 0
           785.1 1694.38
Permanent Ineff=
       F       F
#Block Obstruct= 1 ,-1
     390   437.5 1672.47
Bank Sta=834.4,1117.1
XS Rating Curve= 0 ,0
Exp/Cntr=0.3,0.1
LCMann Table=0

Chan Stop Cuts=-1
Use User Specified Reach Order=0
Composite Channel Slope=5

--- GREENBRRV2.g01 (geometry) ---

Geom Title=USGS 10m DEM
Program Version=4.00

River Reach=GREENBRRV2     ,Main
Reach XY= 30
     2128937.643      276254.605     2127631.777      274839.566
     2127076.221      274360.400     2126853.999      274117.344
     2126465.110      273568.733     2126076.221      273360.400
     2125728.999      273103.455     2125624.832      272943.733
     2125097.054      272540.955     2124534.554      271818.733
     2124208.165      271554.844     2123999.832      271443.733
     2123749.832      271374.288     2123520.665      271360.400
     2123180.388      271492.344     2122701.221      271554.844
     2122319.277      271554.844     2121867.888      271492.344
     2120145.665      270818.733     2119603.999      270540.955
     2118520.665      269735.400     2118360.943      269471.511
     2117902.610      267700.677     2117749.832      267228.455
     2117492.888      266610.400     2117263.721      266277.066
     2117055.388      266047.900     2116145.665      265145.122
     2115819.685      264541.696     2115538.603      264261.840

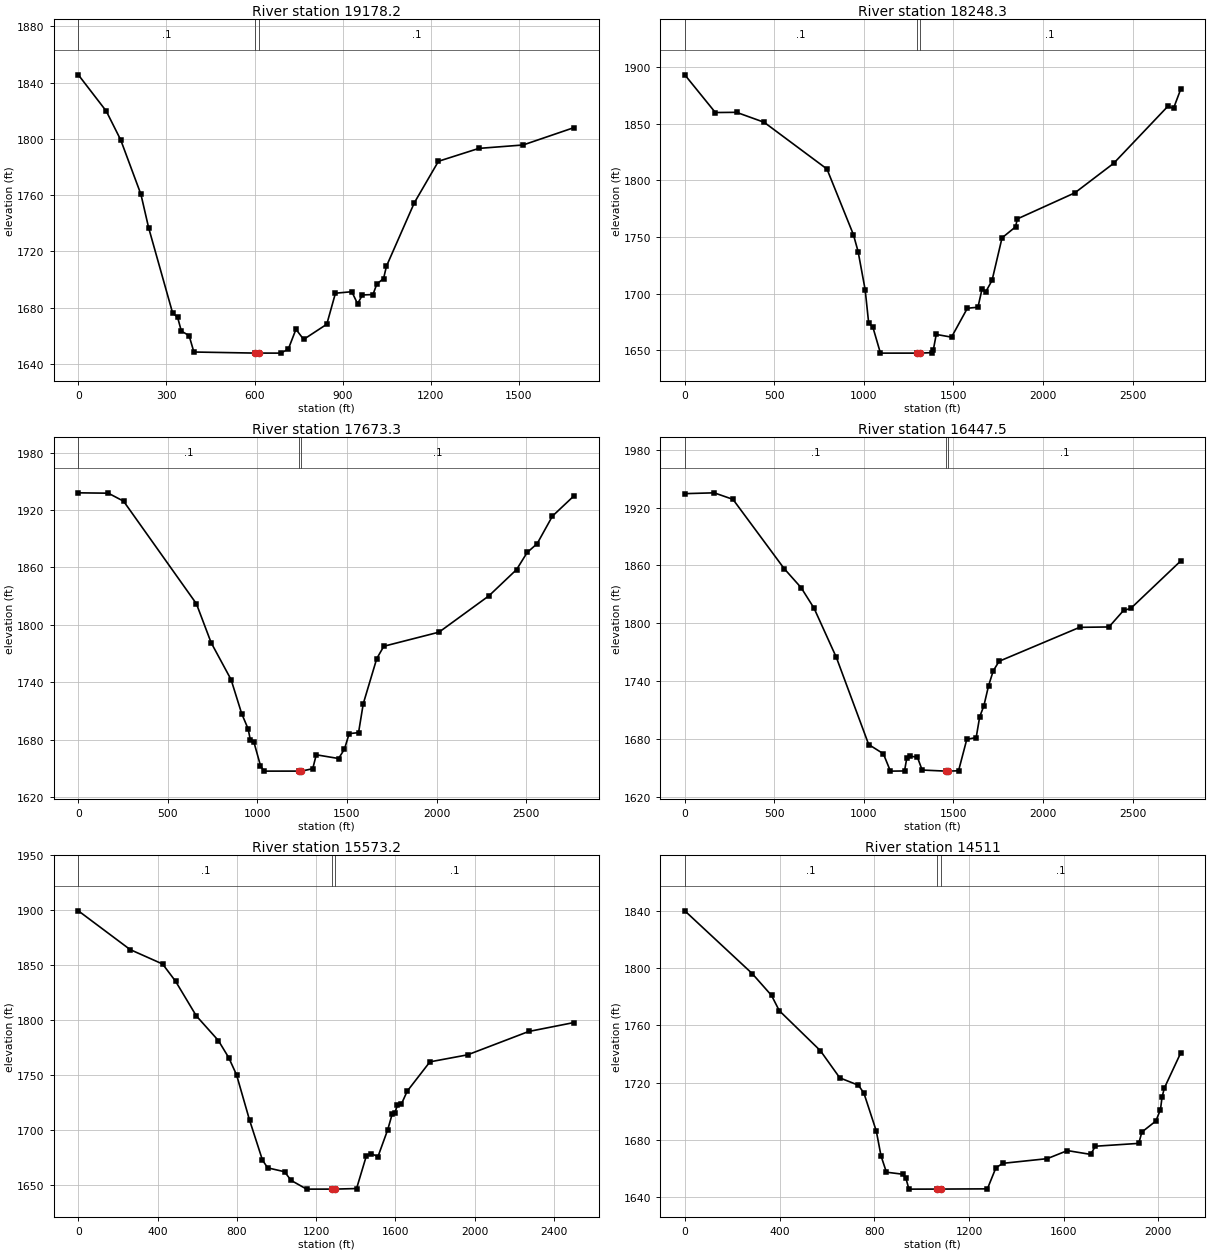
Type RM Length L Ch R = 1 ,19178.2,952.1,929.9,914.4
XS GIS Cut Line= 3
     2129310.994      275761.116     2128542.765      276364.414
     2128571.700      277074.773
#Sta/Elev= 30
       0 1845.48    95.1 1819.68   144.2 1799.22   213.1 1760.49   239.3 1736.78
   321.2 1675.99   337.6 1673.31   350.7 1663.28   377.0 1660.12   393.3 1648.43
     601 1647.67     616 1647.68   688.4 1647.64   714.6 1650.43   740.8 1664.57
   767.0 1657.40   845.7 1668.17   875.2 1690.23   930.9 1691.30   950.6 1682.72
   967.0 1688.97  1003.0 1689.30  1016.1 1696.78  1039.0 1700.65  1048.9 1709.45
  1143.9 1754.59  1225.8 1784.02  1363.4 1793.18  1514.1 1795.61  1687.8 1807.99
#Mann= 3 , 0 , 0
       0     0.1       0     601   0.045       0     616     0.1       0
Bank Sta=601,616
Exp/Cntr=0.3,0.1

Type RM Length L Ch R = 1 ,18248.3,575.2,575.1,575.2
XS GIS Cut Line= 2
     2129144.617      274540.051     2127156.769      276467.134
#Sta/Elev= 30
       0 1893.42   170.6 1860.08   288.7 1860.26   442.8 1851.47   793.8 1810.12
   941.5 1752.08   967.7 1737.16  1007.1 1703.35  1026.8 1673.79  1049.7 1670.52
  1092.4 1647.30  1296.1 1647.31  1311.1 1647.32  1377.7 1647.70  1387.6 1650.07
  1404.0 1663.84  1489.3 1661.43  1577.8 1687.00  1636.9 1687.89  1659.8 1704.06
  1679.5 1701.28  1715.6 1711.60  1771.4 1749.25  1846.8 1758.96  1856.7 1765.99
  2178.2 1789.07  2394.6 1815.14  2696.4 1865.44  2729.2 1863.85  2768.6 1880.48
#Mann= 3 , 0 , 0
       0     0.1       0  1296.1   0.045       0  1311.1     0.1       0
Bank Sta=1296.1,1311.1
Exp/Cntr=0.3,0.1

Type RM Length L Ch R = 1 ,17673.3,1233.8,1225.8,1222.9
XS GIS Cut Line= 2
     2128704.092      274166.284     2126716.245      276093.367
#Sta/Elev= 30
       0 1937.97   167.3 1937.59   252.6 1929.23   659.4 1821.99   741.4 1781.39
   852.9 1742.72   911.9 1707.30   948.0 1691.27   961.1 1679.16   980.8 1677.14
  1016.9 1652.91  1036.6 1647.08    1231 1647.11    1246 1647.11  1308.9 1649.62
  1328.5 1664.16  1453.2 1660.26  1486.0 1670.07  1512.2 1686.27  1564.7 1687.31
  1591.0 1717.54  1666.4 1764.74  1705.8 1777.60  2014.1 1792.35  2293.0 1830.37
  2447.1 1857.76  2506.2 1875.61  2562.0 1884.84  2647.2 1913.60  2768.6 1934.99
#Mann= 3 , 0 , 0
       0     0.1       0    1231   0.045       0    1246     0.1       0
Bank Sta=1231,1246
Exp/Cntr=0.3,0.1

Type RM Length L Ch R = 1 ,16447.5,891.5,874.3,868.8
XS GIS Cut Line= 2
     2127974.013      273172.774     2125986.165      275099.857
#Sta/Elev= 30
       0 1934.57   164.0 1935.42   269.0 1928.64   554.4 1856.87   649.5 1836.99
   721.7 1815.69   846.3 1764.58  1026.8 1674.21  1108.8 1664.62  1148.1 1646.59
  1226.8 1646.76  1240.0 1660.55  1256.4 1662.25  1299.0 1660.95  1325.3 1647.72
  1457.1 1646.60  1472.1 1646.60  1528.6 1646.95  1574.6 1679.57  1627.0 1681.45
  1646.7 1703.02  1669.7 1714.20  1695.9 1735.01  1722.2 1750.63  1755.0 1760.60
  2204.4 1795.81  2368.4 1796.21  2450.4 1813.46  2489.8 1815.38  2768.6 1864.62
#Mann= 3 , 0 , 0
       0     0.1       0  1457.1   0.045       0  1472.1     0.1       0
Bank Sta=1457.1,1472.1
Exp/Cntr=0.3,0.1

Type RM Length L Ch R = 1 ,15573.2,1108,1062.2,1008.5
XS GIS Cut Line= 4
     2127463.772      273238.546     2126810.994      273071.880
     2126112.175      273789.809     2125949.883      274599.657
#Sta/Elev= 30
       0 1899.52   261.6 1864.22   425.2 1851.09   490.6 1835.40   595.2 1803.90
   706.5 1781.44   758.8 1765.88   798.1 1750.30   863.6 1709.17   929.1 1672.55
   955.3 1665.55  1040.4 1662.02  1073.2 1654.17  1151.7 1646.18  1281.9 1646.20
  1296.9 1646.20  1403.8 1646.71  1453.0 1676.34  1475.9 1678.55  1511.9 1675.84
  1561.0 1700.28  1583.9 1714.76  1597.0 1715.84  1610.1 1722.50  1629.8 1723.55
  1659.2 1735.33  1773.9 1762.04  1964.0 1768.43  2272.1 1789.68  2501.6 1797.86
#Mann= 3 , 0 , 0
       0     0.1       0  1281.9   0.045       0  1296.9     0.1       0
Bank Sta=1281.9,1296.9
Exp/Cntr=0.3,0.1

Type RM Length L Ch R = 1 ,14511,826.8,890.9,998.1
XS GIS Cut Line= 4
     2126331.827      272356.602     2125838.772      272384.380
     2125262.383      273377.435     2125241.549      273828.824
#Sta/Elev= 30
       0 1839.88   284.5 1796.12   366.3 1780.84   399.0 1770.21   572.6 1742.29
   654.6 1723.33   733.3 1718.19   756.3 1712.72   808.8 1686.18   828.5 1669.01
   851.4 1657.53   920.3 1656.11   933.4 1653.44   946.6 1645.71  1065.3 1645.74
  1080.3 1645.75  1277.9 1645.90  1314.0 1660.68  1343.5 1663.71  1530.5 1666.97
  1615.8 1672.60  1714.1 1669.94  1733.7 1675.64  1917.1 1677.63  1930.2 1685.53
  1989.1 1693.19  2008.8 1701.21  2015.3 1709.76  2025.2 1716.24  2093.9 1740.60
#Mann= 3 , 0 , 0
       0     0.1       0  1065.3   0.045       0  1080.3     0.1       0
Bank Sta=1065.3,1080.3
Exp/Cntr=0.3,0.1

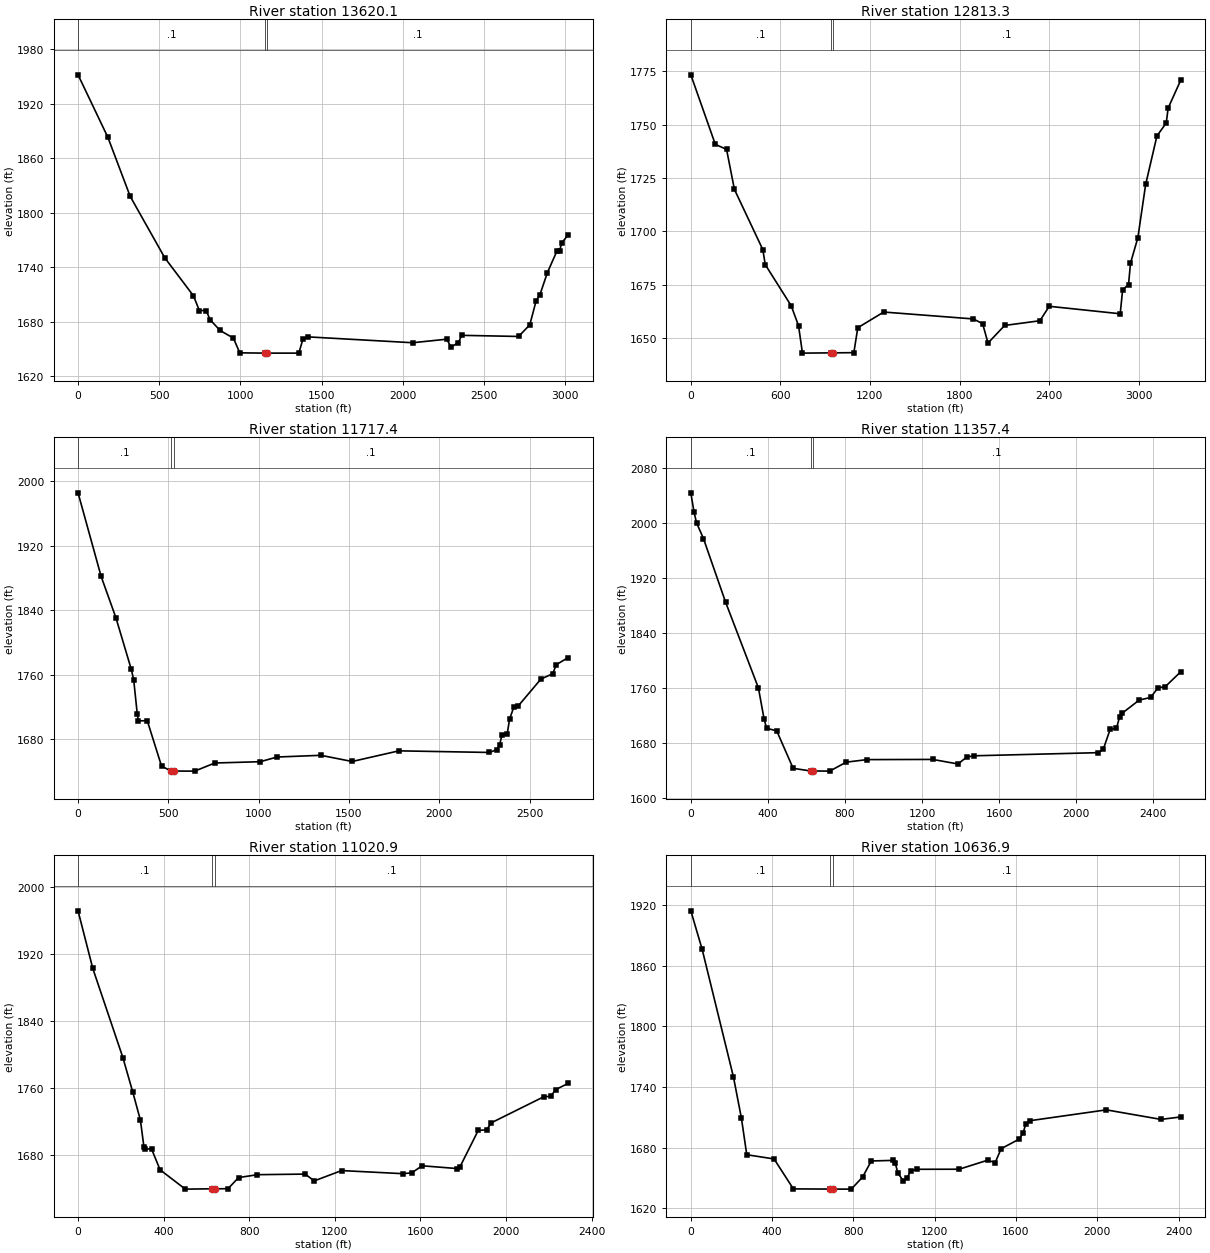
Type RM Length L Ch R = 1 ,13620.1,842.4,806.8,774.2
XS GIS Cut Line= 3
     2125778.440      271547.565     2124334.536      272758.112
     2123984.498      273837.394
#Sta/Elev= 30
       0 1952.02   183.5 1883.27   321.1 1818.12   534.1 1750.44   711.1 1708.48
   747.1 1692.32   789.7 1692.23   812.7 1682.32   874.9 1670.34   956.9 1661.92
   996.2 1645.69  1150.5 1645.38  1165.5 1645.38  1359.9 1645.37  1386.1 1661.39
  1415.6 1663.28  2061.3 1656.82  2271.2 1660.74  2297.4 1651.96  2343.3 1657.05
  2363.0 1664.97  2713.9 1663.74  2782.7 1676.57  2822.1 1703.29  2845.0 1709.67
  2891.0 1734.05  2950.0 1757.94  2966.4 1758.39  2979.5 1766.79  3018.8 1775.67
#Mann= 3 , 0 , 0
       0     0.1       0  1150.5   0.045       0  1165.5     0.1       0
Bank Sta=1150.5,1165.5
Exp/Cntr=0.3,0.1

Type RM Length L Ch R = 1 ,12813.3,1226.7,1095.9,609.3
XS GIS Cut Line= 2
     2124989.631      270974.577     2122824.979      273443.254
#Sta/Elev= 30
       0 1773.31   164.0 1740.73   239.4 1738.38   291.9 1719.66   482.2 1691.43
   498.6 1684.39   672.4 1665.11   721.6 1655.76   747.8 1642.92   935.8 1643.04
   950.8 1643.05  1092.2 1643.14  1118.5 1654.82  1292.3 1662.17  1892.6 1658.94
  1954.9 1656.72  1991.0 1647.63  2102.5 1655.89  2338.7 1658.09  2401.0 1664.86
  2876.6 1661.36  2893.0 1672.65  2932.3 1674.97  2945.5 1685.08  2994.7 1696.93
  3047.1 1721.94  3122.6 1744.66  3184.9 1750.74  3198.0 1757.76  3283.3 1771.00
#Mann= 3 , 0 , 0
       0     0.1       0   935.8   0.045       0   950.8     0.1       0
Bank Sta=935.8,950.8
Exp/Cntr=0.3,0.1

Type RM Length L Ch R = 1 ,11717.4,348.9,360.1,353.5
XS GIS Cut Line= 3
     2123380.438      270898.268     2123331.827      272696.880
     2122706.827      273363.546
#Sta/Elev= 30
       0 1985.60   127.8 1881.79   209.8 1830.38   295.0 1766.24   308.1 1753.37
   327.7 1711.18   334.3 1702.48   383.4 1702.56   462.1 1646.35   514.7 1640.11
   529.7 1640.10   645.6 1640.01   757.1 1650.09  1009.4 1651.74  1101.2 1657.51
  1343.7 1659.66  1517.4 1651.97  1776.3 1665.20  2277.5 1663.19  2316.8 1666.54
  2333.2 1672.13  2346.2 1684.37  2375.7 1686.11  2388.8 1704.44  2411.8 1719.13
  2438.0 1721.23  2562.4 1754.35  2627.9 1760.96  2647.6 1772.21  2713.1 1781.01
#Mann= 3 , 0 , 0
       0     0.1       0   514.7   0.045       0   529.7     0.1       0
Bank Sta=514.7,529.7
Exp/Cntr=0.3,0.1

Type RM Length L Ch R = 1 ,11357.4,311.7,336.5,386.8
XS GIS Cut Line= 3
     2123047.105      270884.380     2122970.716      272731.602
     2122581.827      273307.991
#Sta/Elev= 30
       0 2044.53    16.4 2016.87    29.5 2001.00    65.6 1977.95   180.3 1885.50
   350.8 1760.62   380.2 1715.41   393.4 1701.83   445.8 1698.14   531.0 1643.56
   621.8 1639.69   636.8 1639.69   721.2 1639.46   806.4 1652.50   914.6 1656.22
  1255.5 1656.49  1386.6 1649.88  1432.5 1659.93  1468.6 1661.76  2114.5 1666.33
  2140.7 1670.97  2176.8 1700.26  2209.6 1701.76  2226.0 1718.70  2239.1 1723.74
  2327.6 1742.89  2386.7 1746.70  2426.0 1761.01  2462.1 1762.18  2544.1 1784.32
#Mann= 3 , 0 , 0
       0     0.1       0   621.8   0.045       0   636.8     0.1       0
Bank Sta=621.8,636.8
Exp/Cntr=0.3,0.1

Type RM Length L Ch R = 1 ,11020.9,328.6,384,439.3
XS GIS Cut Line= 3
     2122804.049      270932.991     2122463.772      272745.491
     2122304.049      273162.157
#Sta/Elev= 30
       0 1971.09    68.8 1902.41   209.6 1795.89   255.5 1754.98   291.5 1721.24
   307.9 1689.24   311.2 1687.01   343.9 1686.71   383.2 1662.02   501.2 1638.92
   625.2 1639.30   640.2 1639.30   701.0 1639.44   750.1 1652.68   838.6 1656.16
  1061.3 1656.87  1103.9 1648.74  1231.6 1661.06  1516.6 1657.38  1559.2 1658.32
  1608.3 1666.78  1768.8 1663.54  1785.2 1665.67  1870.2 1708.93  1909.3 1709.72
  1932.1 1718.19  2176.4 1749.14  2209.0 1749.70  2231.8 1757.64  2290.4 1765.14
#Mann= 3 , 0 , 0
       0     0.1       0   625.2   0.045       0   640.2     0.1       0
Bank Sta=625.2,640.2
Exp/Cntr=0.3,0.1

Type RM Length L Ch R = 1 ,10636.9,153,154.1,146.9
XS GIS Cut Line= 2
     2122634.779      270944.275     2121482.001      273062.331
#Sta/Elev= 30
       0 1914.26    55.7 1876.14   209.7 1749.83   249.0 1708.96   275.2 1672.85
   409.6 1668.67   504.6 1639.02   685.6 1638.86   700.6 1638.85   789.6 1638.80
   845.3 1650.79   887.9 1666.66   992.8 1667.24  1005.9 1664.39  1019.0 1654.65
  1045.2 1646.99  1064.8 1649.93  1081.2 1656.70  1114.0 1658.44  1320.4 1658.51
  1461.3 1667.48  1497.3 1664.89  1526.8 1678.83  1615.3 1688.25  1634.9 1694.32
  1648.0 1703.32  1671.0 1706.60  2044.5 1717.26  2313.2 1707.82  2411.4 1710.25
#Mann= 3 , 0 , 0
       0     0.1       0   685.6   0.045       0   700.6     0.1       0
Bank Sta=685.6,700.6
Exp/Cntr=0.3,0.1

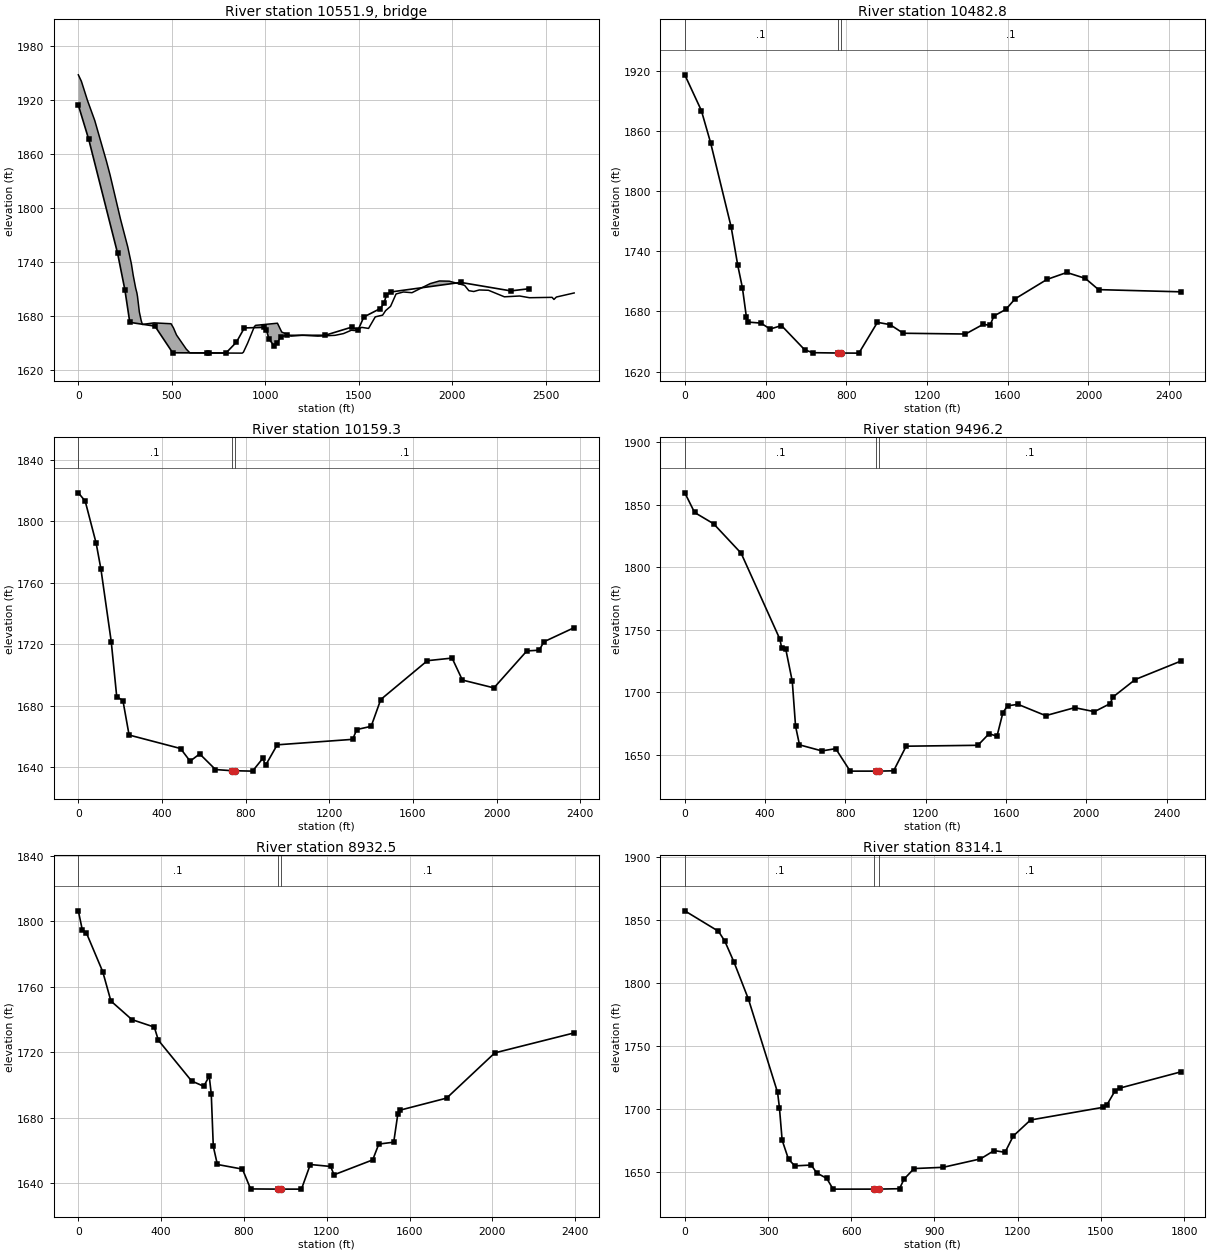
Type RM Length L Ch R = 3 ,10551.9  ,,,
Deck Dist Width WeirC Skew NumUp NumDn MinLoCord MaxHiCord MaxSubmerge Is_Ogee
0.5,0.5,2.6,, 60, 60, , , , 0, ,,,
       0    16.3    48.9    88.1   150.1   169.7   225.1   264.3   283.9   293.6
   306.7   313.2   316.5   326.3   336.1   342.6   404.6   495.9   508.9   525.1
   577.2   596.7   876.2   882.7   905.4   941.1   947.6  1064.8  1087.7  1136.8
  1198.9  1280.6  1372.2  1418.0  1460.5  1476.8  1516.1  1552.1  1588.0  1627.3
  1643.6  1669.8  1699.2  1738.5  1784.2  1882.4  1931.5  1983.9  2065.7  2088.6
  2114.8  2144.3  2193.4  2278.5  2360.3  2412.7  2533.8  2543.6  2556.7  2651.7
 1947.98 1940.84 1919.53 1897.03 1852.14 1836.75 1787.92 1756.68 1737.76 1725.00
 1710.86 1705.57 1701.55 1684.41 1674.93 1670.54 1672.28 1671.32 1666.63 1658.79
 1643.12 1638.94 1638.65 1639.62 1649.76 1667.93 1669.52 1671.90 1662.13 1657.56
 1658.64 1657.56 1658.41 1660.36 1664.13 1663.75 1667.26 1666.12 1678.96 1680.87
 1685.95 1690.64 1704.42 1706.62 1705.82 1715.98 1718.86 1718.60 1713.98 1708.05
 1707.14 1708.86 1708.51 1701.26 1702.14 1700.24 1700.65 1698.32 1701.01 1705.53
                                                                                
                                                                                
                                                                                
                                                                                
                                                                                
                                                                                
       0    16.3    48.9    88.1   150.1   169.7   225.1   264.3   283.9   293.6
   306.7   313.2   316.5   326.3   336.1   342.6   404.6   495.9   508.9   525.1
   577.2   596.7   876.2   882.7   905.4   941.1   947.6  1064.8  1087.7  1136.8
  1198.9  1280.6  1372.2  1418.0  1460.5  1476.8  1516.1  1552.1  1588.0  1627.3
  1643.6  1669.8  1699.2  1738.5  1784.2  1882.4  1931.5  1983.9  2065.7  2088.6
  2114.8  2144.3  2193.4  2278.5  2360.3  2412.7  2533.8  2543.6  2556.7  2651.7
 1947.98 1940.84 1919.53 1897.03 1852.14 1836.75 1787.92 1756.68 1737.76 1725.00
 1710.86 1705.57 1701.55 1684.41 1674.93 1670.54 1672.28 1671.32 1666.63 1658.79
 1643.12 1638.94 1638.65 1639.62 1649.76 1667.93 1669.52 1671.90 1662.13 1657.56
 1658.64 1657.56 1658.41 1660.36 1664.13 1663.75 1667.26 1666.12 1678.96 1680.87
 1685.95 1690.64 1704.42 1706.62 1705.82 1715.98 1718.86 1718.60 1713.98 1708.05
 1707.14 1708.86 1708.51 1701.26 1702.14 1700.24 1700.65 1698.32 1701.01 1705.53
                                                                                
                                                                                
                                                                                
                                                                                
                                                                                
                                                                                
BR Coef=-1 , 0 , 0 ,, 0 ,,,0.8,-1,,0,
WSPro=,,,, 1 ,,,, 0 ,,,, 0 ,,,,-1 ,-1 ,-1 , 0 , 0 , 0 , 0 , 0
BC Design=,, 0 ,, 0 ,,0,,,,
BC HTab HWMax=0
BC HTab TWMax=0
BC HTab MaxSwellHead=0
BC HTab MaxFlow=0
BC User HTab FreeFlow(D)= 0

Type RM Length L Ch R = 1 ,10482.8,321.5,323.5,320.8
XS GIS Cut Line= 2
     2122526.272      270870.491     2121317.938      273009.380
#Sta/Elev= 30
       0 1915.69    82.0 1880.14   127.9 1848.02   229.6 1764.21   262.4 1725.92
   285.4 1703.61   305.0 1674.72   311.6 1669.44   377.2 1668.38   423.1 1662.44
   478.9 1665.96   593.6 1641.88   633.0 1638.92   756.9 1638.59   771.9 1638.58
   862.6 1638.48   954.4 1669.16  1016.8 1666.88  1082.4 1658.28  1390.7 1657.51
  1479.2 1667.25  1512.0 1666.07  1531.7 1675.48  1590.7 1682.04  1636.6 1692.58
  1794.1 1711.86  1892.5 1718.81  1984.3 1712.94  2049.9 1701.73  2456.6 1699.55
#Mann= 3 , 0 , 0
       0     0.1       0   756.9   0.045       0   771.9     0.1       0
Bank Sta=756.9,771.9
Exp/Cntr=0.3,0.1

Type RM Length L Ch R = 1 ,10159.3,687.5,663,647.3
XS GIS Cut Line= 2
     2122185.994      270828.824     2121054.049      272912.157
#Sta/Elev= 30
       0 1818.55    32.8 1813.17    85.3 1785.72   108.2 1768.83   157.4 1721.72
   183.6 1685.96   213.2 1683.46   242.7 1661.03   488.6 1652.26   534.5 1644.04
   580.4 1648.75   655.9 1638.58   733.5 1637.82   748.5 1637.80   833.0 1637.55
   882.2 1645.87   895.3 1641.31   951.0 1654.66  1311.8 1658.22  1331.4 1664.59
  1400.3 1666.69  1446.2 1684.13  1669.2 1709.39  1787.3 1711.07  1836.4 1696.80
  1987.3 1691.69  2144.7 1715.72  2203.7 1716.20  2226.7 1721.70  2371.0 1730.85
#Mann= 3 , 0 , 0
       0     0.1       0   733.5   0.045       0   748.5     0.1       0
Bank Sta=733.5,748.5
Exp/Cntr=0.3,0.1

Type RM Length L Ch R = 1 ,9496.2,553,563.7,571.6
XS GIS Cut Line= 3
     2121797.105      270557.991     2121387.383      270794.102
     2120665.161      272655.213
#Sta/Elev= 30
       0 1859.69    48.9 1843.94   143.5 1834.91   280.5 1811.36   472.9 1742.75
   482.7 1735.50   502.4 1734.86   535.2 1708.84   551.6 1672.80   571.2 1657.92
   682.7 1653.06   751.5 1654.86   823.6 1636.88   954.6 1636.89   969.6 1636.89
  1040.0 1637.14  1102.3 1656.84  1459.6 1657.56  1515.3 1666.84  1554.6 1664.82
  1584.1 1683.64  1607.1 1689.18  1659.5 1690.34  1797.2 1681.30  1941.4 1687.68
  2039.8 1684.49  2118.5 1690.94  2131.6 1696.11  2243.0 1710.20  2469.2 1724.90
#Mann= 3 , 0 , 0
       0     0.1       0   954.6   0.045       0   969.6     0.1       0
Bank Sta=954.6,969.6
Exp/Cntr=0.3,0.1

Type RM Length L Ch R = 1 ,8932.5,571.2,618.4,639.1
XS GIS Cut Line= 3
     2121449.883      270655.213     2120845.716      270703.824
     2120081.827      272321.880
#Sta/Elev= 30
       0 1806.47    19.7 1794.52    39.3 1792.87   118.0 1769.27   157.3 1751.41
   258.8 1740.05   367.0 1735.47   386.6 1727.45   547.2 1702.56   606.1 1699.31
   632.3 1705.56   642.2 1694.66   652.0 1662.65   671.7 1651.57   792.9 1648.74
   832.2 1636.64   962.9 1636.53   977.9 1636.53  1078.0 1636.52  1120.6 1651.55
  1218.9 1650.36  1235.3 1645.27  1422.1 1654.37  1451.6 1664.04  1523.7 1665.18
  1543.4 1682.30  1553.2 1684.71  1779.3 1692.10  2012.0 1719.72  2395.4 1731.92
#Mann= 3 , 0 , 0
       0     0.1       0   962.9   0.045       0   977.9     0.1       0
Bank Sta=962.9,977.9
Exp/Cntr=0.3,0.1

Type RM Length L Ch R = 1 ,8314.1,695.1,682.1,681.2
XS GIS Cut Line= 2
     2120567.938      270280.213     2119401.272      271634.380
#Sta/Elev= 30
       0 1856.90   121.4 1840.67   144.3 1832.81   177.1 1816.32   229.6 1786.71
   334.5 1712.78   341.1 1700.78   350.9 1674.98   373.9 1659.77   396.8 1654.55
   455.9 1655.21   475.6 1648.95   511.6 1644.66   534.6 1636.11   683.7 1636.12
   698.7 1636.12   774.0 1636.44   790.4 1644.06   826.5 1652.43   931.4 1653.42
  1065.9 1660.10  1115.1 1666.70  1154.4 1665.32  1184.0 1678.22  1246.3 1690.96
  1508.6 1701.04  1521.8 1703.04  1551.3 1714.18  1567.7 1716.23  1787.4 1729.09
#Mann= 3 , 0 , 0
       0     0.1       0   683.7   0.045       0   698.7     0.1       0
Bank Sta=683.7,698.7
Exp/Cntr=0.3,0.1

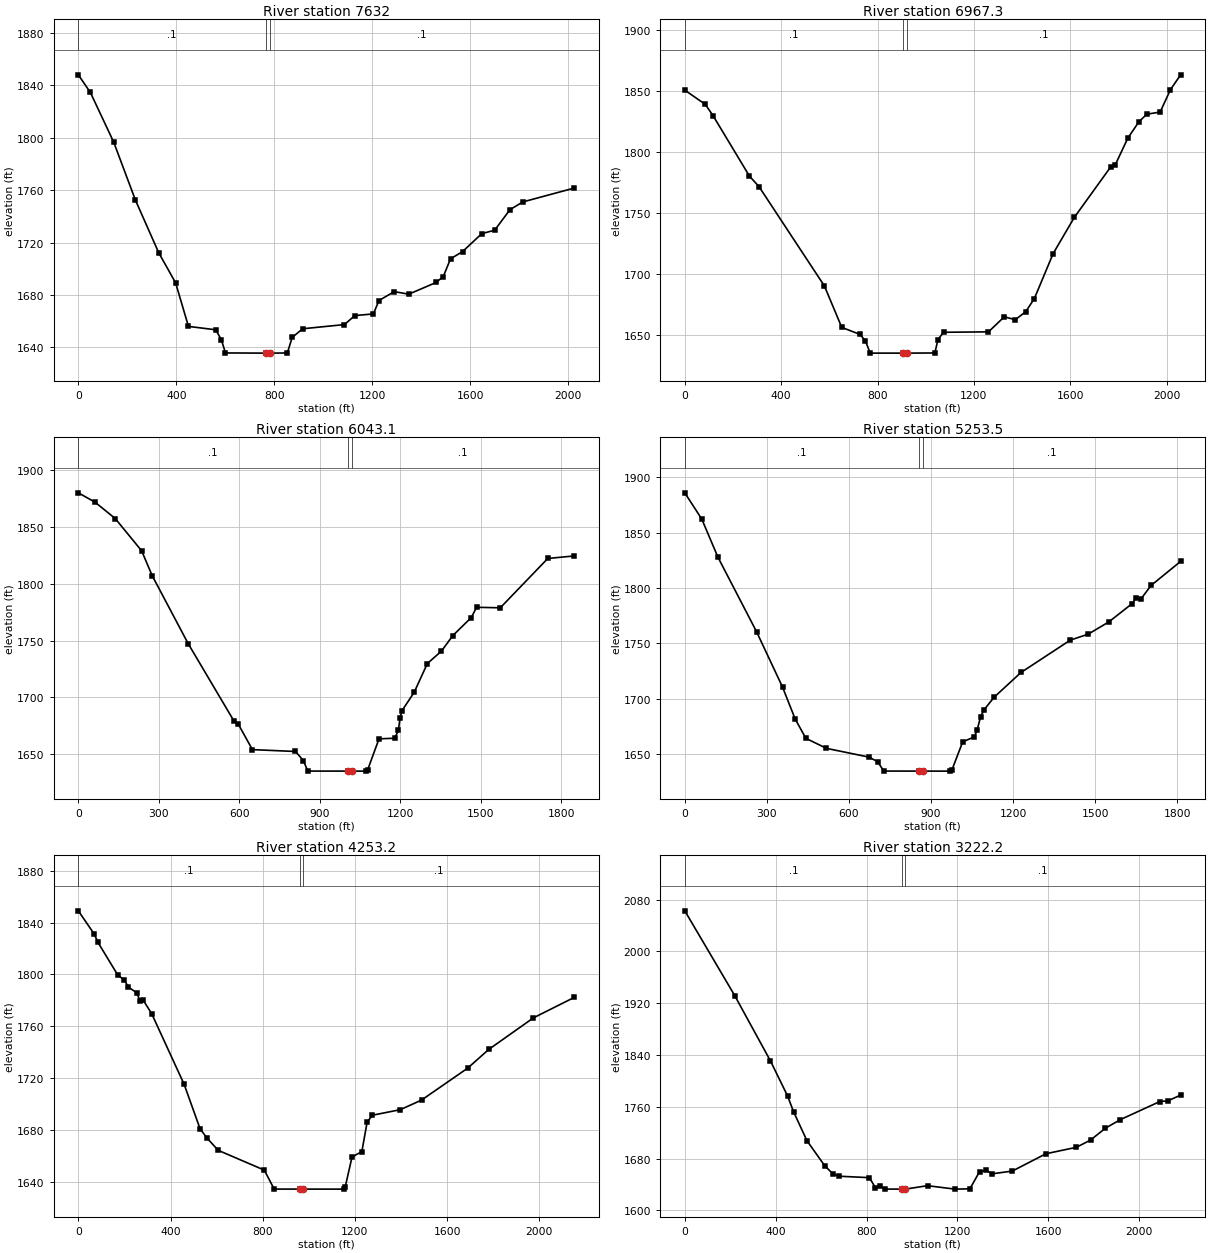
Type RM Length L Ch R = 1 ,7632,665,664.7,666.2
XS GIS Cut Line= 3
     2119977.661      269849.657     2119095.716      271057.991
     2118908.216      271551.046
#Sta/Elev= 30
       0 1847.77    49.2 1834.32   144.4 1796.46   232.9 1752.36   328.1 1712.17
   397.0 1689.28   449.4 1656.06   561.0 1653.48   584.0 1645.72   600.4 1635.84
   766.5 1635.70   781.5 1635.70   853.0 1635.82   872.6 1647.62   915.3 1654.26
  1085.9 1657.45  1128.5 1664.32  1204.0 1665.59  1227.0 1675.79  1289.3 1682.58
  1348.3 1680.61  1459.9 1689.52  1489.4 1694.05  1518.9 1707.54  1568.0 1713.07
  1646.7 1726.77  1699.1 1729.36  1761.4 1744.98  1813.8 1750.91  2023.5 1761.46
#Mann= 3 , 0 , 0
       0     0.1       0   766.5   0.045       0   781.5     0.1       0
Bank Sta=766.5,781.5
Exp/Cntr=0.3,0.1

Type RM Length L Ch R = 1 ,6967.3,810.1,924.3,981.8
XS GIS Cut Line= 3
     2119533.216      269328.824     2118665.161      270523.268
     2118158.216      270807.991
#Sta/Elev= 30
       0 1850.51    85.1 1838.86   117.9 1829.43   268.5 1780.12   307.8 1771.63
   579.5 1690.27   651.5 1656.40   726.8 1650.68   749.7 1645.44   769.4 1635.35
   907.7 1635.34   922.7 1635.34  1037.8 1635.47  1050.9 1646.48  1073.9 1652.41
  1260.5 1652.74  1326.0 1665.06  1371.8 1662.70  1414.4 1669.13  1450.4 1679.75
  1528.8 1716.75  1617.0 1746.48  1767.3 1787.57  1786.9 1789.50  1839.1 1811.34
  1884.9 1824.62  1917.5 1830.82  1973.1 1832.58  2015.5 1850.83  2058.0 1863.04
#Mann= 3 , 0 , 0
       0     0.1       0   907.7   0.045       0   922.7     0.1       0
Bank Sta=907.7,922.7
Exp/Cntr=0.3,0.1

Type RM Length L Ch R = 1 ,6043.1,756.5,789.6,802.6
XS GIS Cut Line= 2
     2119283.216      269044.102     2117581.827      269766.324
#Sta/Elev= 30
       0 1880.09    62.3 1871.85   137.6 1857.43   236.0 1829.00   275.3 1807.12
   409.6 1747.18   580.1 1679.09   596.4 1676.25   648.9 1653.87   809.5 1652.24
   839.0 1644.19   855.3 1634.98  1005.3 1634.95  1020.3 1634.94  1071.6 1634.93
  1078.2 1635.83  1120.8 1663.37  1179.8 1663.92  1192.9 1670.96  1199.4 1681.61
  1206.0 1688.04  1251.9 1704.34  1301.0 1729.70  1353.5 1740.64  1396.1 1754.36
  1464.9 1770.24  1484.6 1779.24  1573.0 1778.82  1750.0 1822.26  1848.3 1824.49
#Mann= 3 , 0 , 0
       0     0.1       0  1005.3   0.045       0  1020.3     0.1       0
Bank Sta=1005.3,1020.3
Exp/Cntr=0.3,0.1

Type RM Length L Ch R = 1 ,5253.5,1009.5,1000.3,993.6
XS GIS Cut Line= 3
     2118998.494      268474.657     2117713.772      268780.213
     2117463.772      269203.824
#Sta/Elev= 30
       0 1885.88    62.3 1862.06   121.2 1827.71   262.2 1760.52   357.2 1710.49
   403.0 1681.88   442.4 1664.23   517.7 1655.15   671.8 1647.31   704.5 1643.22
   727.4 1634.64   857.1 1634.61   872.1 1634.60   969.9 1634.58   976.5 1635.69
  1015.8 1661.01  1058.4 1665.53  1068.2 1671.38  1081.4 1683.85  1094.5 1690.16
  1130.5 1701.28  1228.8 1723.64  1409.1 1752.87  1474.7 1758.27  1550.1 1769.33
  1635.4 1785.89  1648.5 1790.60  1668.2 1790.31  1704.2 1802.20  1812.4 1823.97
#Mann= 3 , 0 , 0
       0     0.1       0   857.1   0.045       0   872.1     0.1       0
Bank Sta=857.1,872.1
Exp/Cntr=0.3,0.1

Type RM Length L Ch R = 1 ,4253.2,1058.1,1031,971.9
XS GIS Cut Line= 3
     2118831.827      267426.046     2117456.827      267842.713
     2117151.272      268488.546
#Sta/Elev= 30
       0 1849.10    68.9 1831.16    85.3 1824.68   170.6 1799.66   200.1 1795.54
   216.5 1790.32   252.6 1785.89   269.0 1779.20   282.1 1779.90   318.2 1769.68
   459.2 1715.03   528.1 1680.79   557.6 1673.74   606.8 1664.12   806.9 1648.85
   849.6 1634.20   961.7 1634.19   976.7 1634.18  1151.4 1634.16  1157.9 1635.80
  1187.4 1658.98  1230.1 1663.16  1253.0 1685.94  1276.0 1691.23  1397.4 1695.55
  1489.2 1702.96  1689.1 1727.58  1780.9 1742.08  1974.2 1766.41  2151.2 1782.20
#Mann= 3 , 0 , 0
       0     0.1       0   961.7   0.045       0   976.7     0.1       0
Bank Sta=961.7,976.7
Exp/Cntr=0.3,0.1

Type RM Length L Ch R = 1 ,3222.2,801.6,790.2,764.5
XS GIS Cut Line= 2
     2118380.438      266245.491     2116505.438      267363.546
#Sta/Elev= 30
       0 2062.53   219.6 1931.78   377.0 1830.91   452.3 1776.86   478.6 1752.61
   537.6 1707.74   616.2 1668.90   652.3 1656.38   678.5 1652.82   812.9 1650.56
   839.1 1635.15   858.8 1637.60   881.7 1632.93   956.3 1632.92   971.3 1632.92
  1068.6 1638.18  1189.9 1632.87  1255.4 1633.36  1298.0 1660.08  1327.5 1661.63
  1353.8 1656.55  1442.2 1660.78  1589.8 1687.48  1724.1 1697.45  1786.4 1708.64
  1852.0 1726.95  1917.5 1740.14  2091.3 1768.06  2127.3 1769.20  2183.0 1778.04
#Mann= 3 , 0 , 0
       0     0.1       0   956.3   0.045       0   971.3     0.1       0
Bank Sta=956.3,971.3
Exp/Cntr=0.3,0.1