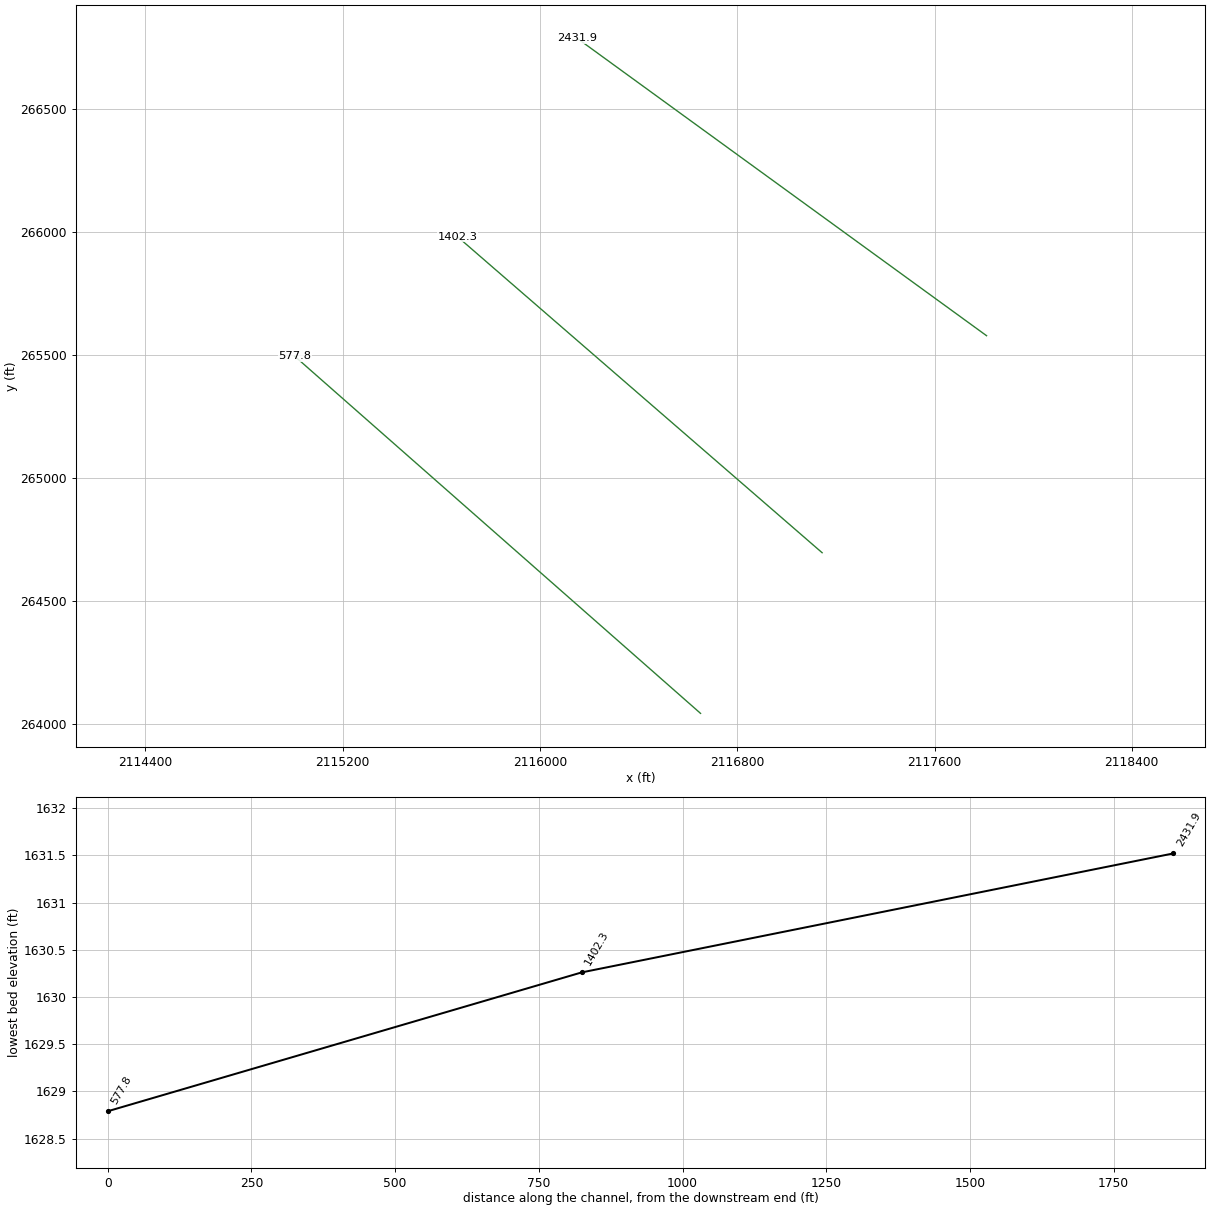
HEC-RAS study GREENBRRV2.prj: GREENBRRV2

--- GREENBRRV2.g01 (geometry) --- (continued)

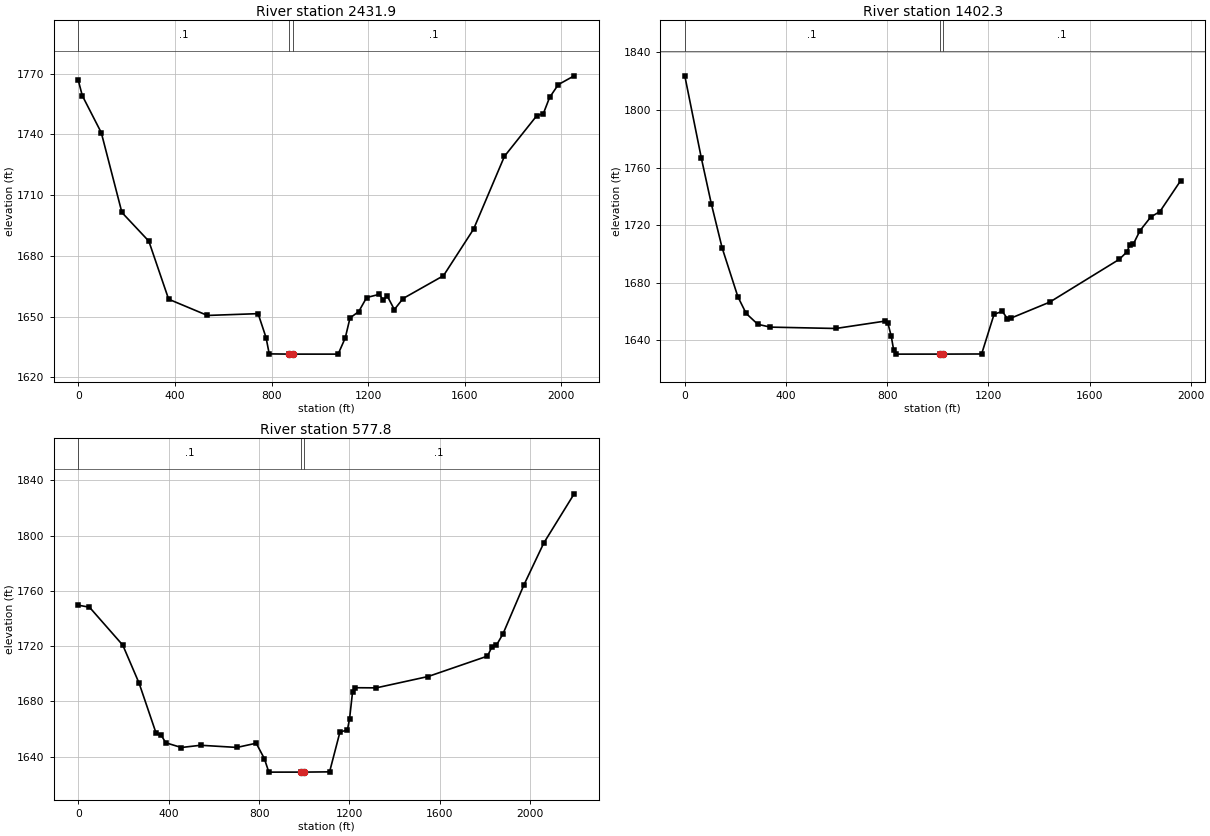
Type RM Length L Ch R = 1 ,2431.9,1059.8,1029.6,1007.5
XS GIS Cut Line= 2
     2117810.994      265578.824     2116151.272      266787.157
#Sta/Elev= 30
       0 1766.60    16.4 1759.11    95.1 1740.82   180.4 1701.44   291.9 1687.28
   373.9 1658.63   534.6 1650.61   744.4 1651.50   777.2 1639.70   790.4 1631.64
   872.3 1631.53   887.3 1631.53  1075.7 1631.52  1105.2 1639.52  1124.9 1649.38
  1161.0 1652.52  1193.8 1659.46  1246.2 1661.03  1262.6 1658.14  1279.0 1660.23
  1308.5 1653.52  1344.6 1658.97  1511.9 1670.23  1636.5 1693.21  1764.4 1729.17
  1898.8 1749.29  1925.1 1750.14  1951.3 1758.22  1987.4 1764.56  2053.0 1768.89
#Mann= 3 , 0 , 0
       0     0.1       0   872.3   0.045       0   887.3     0.1       0
Bank Sta=872.3,887.3
Exp/Cntr=0.3,0.1

Type RM Length L Ch R = 1 ,1402.3,814.1,824.6,812.1
XS GIS Cut Line= 2
     2117144.327      264696.880     2115665.161      265981.602
#Sta/Elev= 30
       0 1823.77    65.5 1766.45   104.8 1734.79   147.4 1704.22   209.7 1670.17
   242.4 1658.56   288.3 1651.02   337.4 1649.04   596.3 1648.09   792.8 1653.27
   802.7 1651.63   815.8 1642.67   825.6 1632.79   835.4 1630.26  1006.7 1630.28
  1021.7 1630.28  1172.9 1630.36  1222.0 1657.95  1254.8 1660.03  1274.5 1654.90
  1290.8 1655.44  1441.6 1666.39  1716.8 1696.18  1746.2 1701.21  1759.3 1706.34
  1772.4 1706.82  1798.7 1716.13  1841.2 1725.62  1877.3 1729.38  1959.2 1750.84
#Mann= 3 , 0 , 0
       0     0.1       0  1006.7   0.045       0  1021.7     0.1       0
Bank Sta=1006.7,1021.7
Exp/Cntr=0.3,0.1

Type RM Length L Ch R = 1 ,577.8,658.1,577.8,595.9
XS GIS Cut Line= 2
     2116651.272      264044.102     2115005.438      265495.491
#Sta/Elev= 30
       0 1749.64    49.2 1748.22   196.8 1720.71   269.0 1693.15   344.4 1656.86
   367.4 1655.31   387.0 1650.04   455.9 1646.62   541.2 1648.24   701.9 1646.67
   787.2 1649.72   823.3 1638.57   843.0 1628.79   984.6 1628.81   999.6 1628.81
  1112.0 1628.99  1157.9 1657.87  1190.7 1659.26  1200.5 1667.54  1213.6 1686.76
  1223.5 1689.91  1318.6 1689.80  1548.2 1698.02  1810.6 1712.79  1830.3 1719.34
  1850.0 1720.57  1879.5 1728.93  1971.3 1764.06  2059.9 1794.65  2194.4 1830.29
#Mann= 3 , 0 , 0
       0     0.1       0   984.6   0.045       0   999.6     0.1       0
Bank Sta=984.6,999.6
Exp/Cntr=0.3,0.1